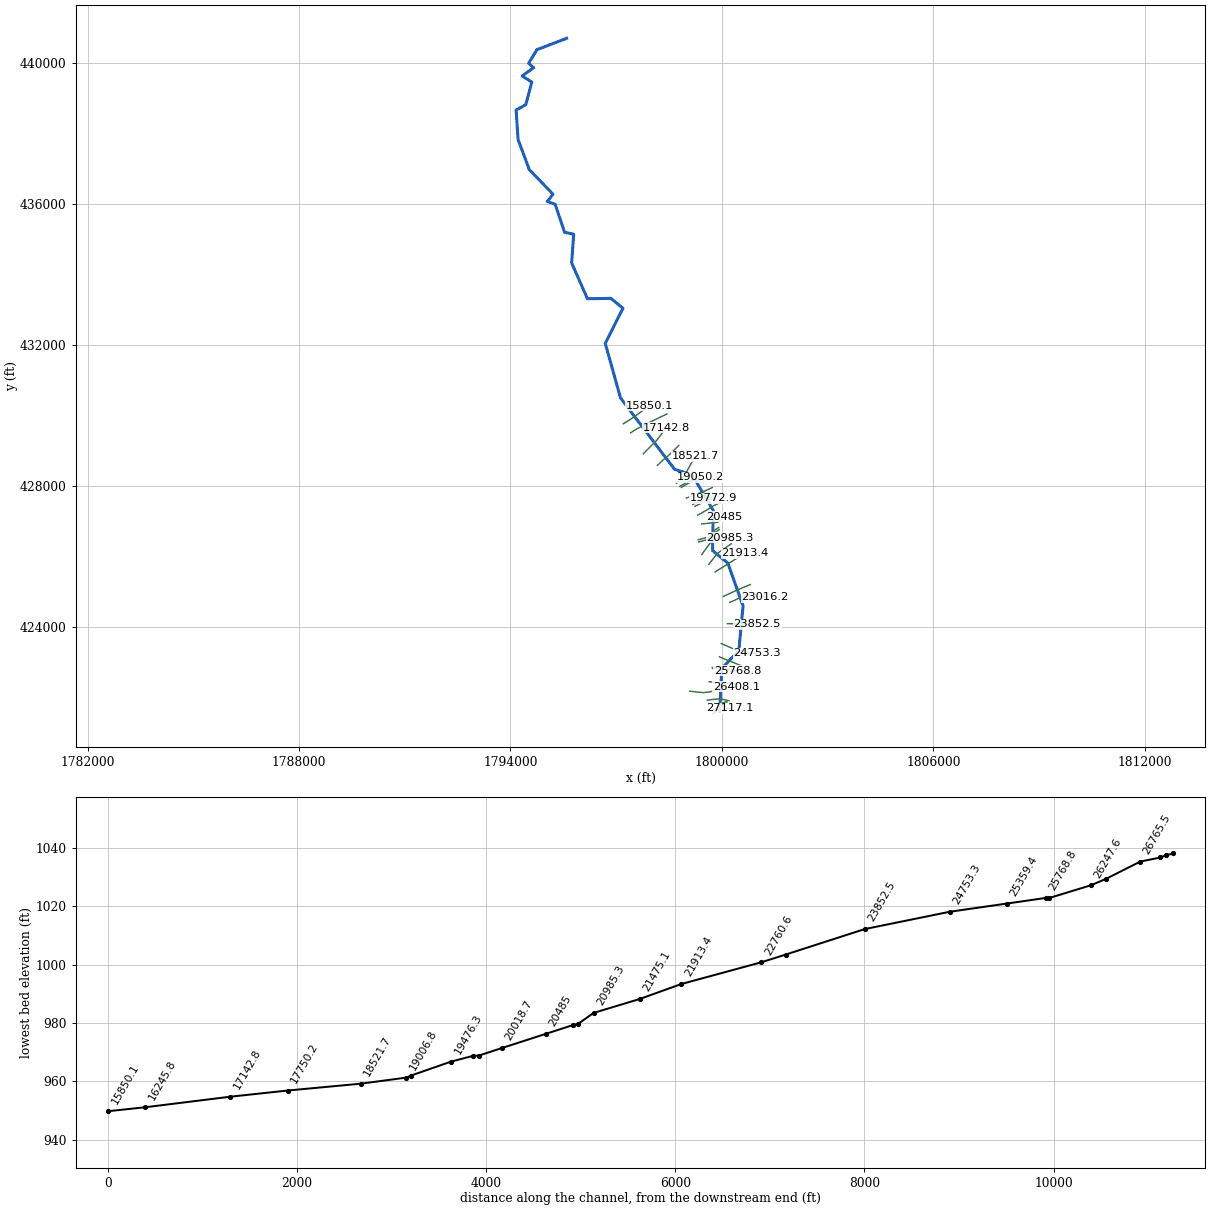
--- DollsRun.prj (project) ---

Proj Title=DollsRun
Current Plan=p01
Default Exp/Contr=0,0
English Units
Geom File=g01
Flow File=f01
Plan File=p01
BEGIN DESCRIPTION:
END DESCRIPTION:
DSS Export Rating Curves= 0
DSS Export Rating Curve Sorted= 0
DSS Export Volume Flow Curves= 0
DXF OffsetX= 0
DXF OffsetY= 0
DXF ScaleX= 0
DXF ScaleY= 0

--- DollsRun.p01 (plan) ---

Plan Title=Floodplain
Program Version=4.00
Geom File=g01
Flow File=f01
K Sum by GR=0
Std Step Tol=0.01
Critical Tol=0.01
Num of Std Step Trials=20
Max Error Tol=0.3
Flow Tol Ratio=0.001
Split Flow NTrial=30
Split Flow Tol=0.02
Split Flow Ratio=0.02
Log Output Level=0
Friction Slope Method=1
Unsteady Friction Slope Method=2
Unsteady Bridges Friction Slope Method=1
Global Log Level=0
CheckData=False
Run HTab=0
Run UNet=0
Run PostProcess=0
UNET Theta=0
UNET Theta Warmup=0
UNET ZTol=0
UNET ZSATol=0
UNET MxIter=0
UNET MaxInSteps=0
UNET DtIC=0
UNET DtMin=0
UNET MaxCRTS=0
UNET WFStab=0
UNET SFStab=0
UNET WFX=0
UNET SFX=0
UNET DSS MLevel=0
UNET DZMax Abort=0
UNET Convert EG Bridges=0
UNET Use Existing IB Tables=0
UNET Froude Limit=0
UNET Froude Power=0
Write IC File=0
Echo Input=False
Echo Output=False
Write Detailed=0

--- DollsRun.f01 (steady flow) ---

Flow Title=NFF Regression Equation
Program Version=4.10
Number of Profiles= 1
Profile Names=P100yr
River Rch & RM=DollsRun,Main            ,27117.1
     636
River Rch & RM=DollsRun,Main            ,26408.1
     827
River Rch & RM=DollsRun,Main            ,24753.3
     864
River Rch & RM=DollsRun,Main            ,23016.2
     934
River Rch & RM=DollsRun,Main            ,22760.6
    1057
River Rch & RM=DollsRun,Main            ,20985.3
    1155
River Rch & RM=DollsRun,Main            ,19476.3
    1243
River Rch & RM=DollsRun,Main            ,18521.7
    1330
River Rch & RM=DollsRun,Main            ,16245.8
    1376
River Rch & RM=DollsRun,Main            ,15850.1
    1576
River Rch & RM=DollsRun,Main            ,15269.7
    1583
River Rch & RM=DollsRun,Main            ,14971.1
    2385
River Rch & RM=DollsRun,Main            ,8360.5
    2601
River Rch & RM=DollsRun,Main            ,6365.3
    2626
River Rch & RM=DollsRun,Main            ,269.7
    2801
Boundary for River Rch & Prof#=DollsRun,Main            , 1
Up Type= 0
Dn Type= 3
Dn Slope=0.00316
DSS Import GetInterval= 0
DSS Import GetPeak= 0
DSS Import FillOption= 0

--- DollsRun.g01 (geometry) ---

Geom Title=USGS 10m DEM
Program Version=4.10

River Reach=DollsRun        ,Main
Reach XY= 30
     1799937.729      421589.983     1799995.953      422815.358
     1800479.367      423310.522     1800600.801      424585.963
     1800166.648      425803.324     1799735.051      426154.887
     1799754.148      427294.296     1799156.926       428305.06
     1798655.537      428462.873     1797121.862      430489.604
     1796689.396      432038.562     1797192.348       433033.18
      1796850.16      433313.562     1796183.841      433304.013
     1795735.577      434319.118     1795793.737      435135.263
     1795535.056      435187.347     1795268.389      435983.006
     1795044.431      436063.735     1795205.889      436270.333
     1794532.626       436970.68     1794215.612      437821.027
     1794159.188      438657.138     1794436.098      438813.388
     1794604.501      439452.451     1794329.327      439626.583
      1794658.32      439859.569     1794515.091      439986.305
     1794750.334      440372.243     1795591.005      440693.872

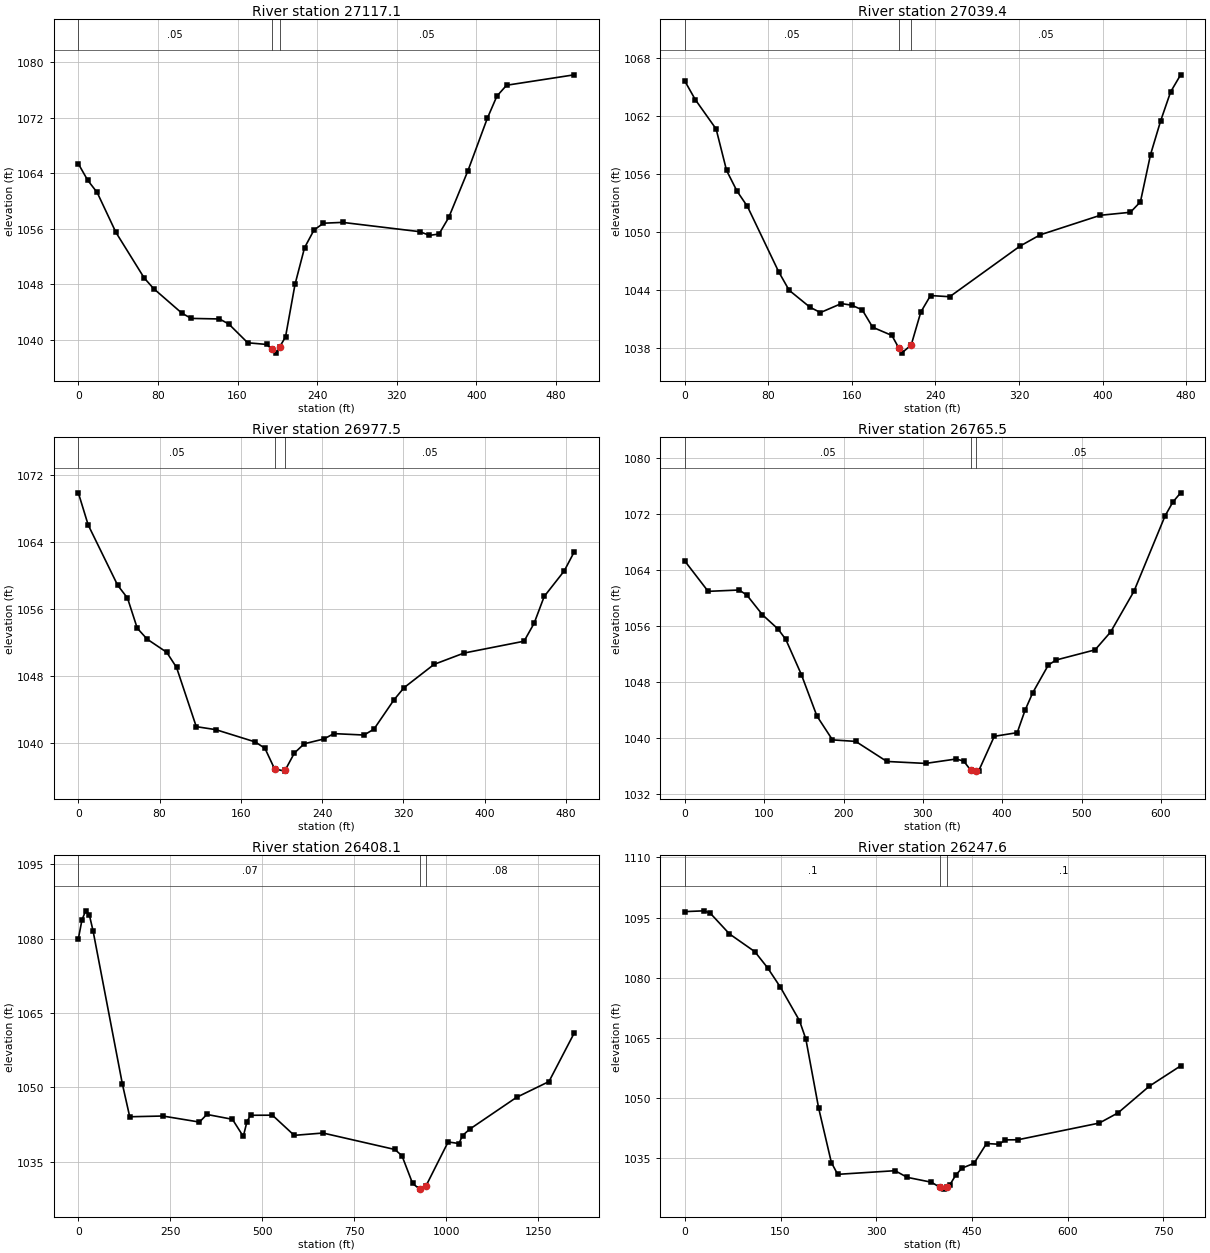
Type RM Length L Ch R = 1 ,27117.1 ,53,77.7,96.8
XS GIS Cut Line= 4
     1799750.257      421536.213     1799905.205      421606.525
     1799985.934      421635.171     1800222.913      421685.952
#Sta/Elev= 30
       0 1065.37     9.4    1063    18.9 1061.24    37.8 1055.48    66.2 1048.92
    75.6  1047.4     104 1043.86   113.4  1043.1   141.8 1043.02   151.2 1042.29
   170.2 1039.59   189.2 1039.35  194.451038.661   198.7  1038.1  202.451039.028
   208.2 1040.45   217.7 1047.99   227.3 1053.28   236.8 1055.83   246.3 1056.81
   265.5 1056.93   343.1 1055.59   352.8 1055.06   362.4 1055.25   372.2 1057.64
   391.5 1064.38   410.9  1071.9   420.6 1075.12   430.3 1076.68   498.2 1078.18
#Mann= 3 , 0 , 0
       0     .05       0  194.45    .045       0  202.45     .05       0
Bank Sta=194.45,202.45
XS Rating Curve= 0 ,0
Exp/Cntr=0.3,0.1

Type RM Length L Ch R = 1 ,27039.4 ,67.9,61.9,65.9
XS GIS Cut Line= 4
     1799750.257      421585.692     1799911.715      421664.945
     1799948.043      421729.268     1800141.663      421835.909
#Sta/Elev= 30
       0 1065.63      10 1063.71      30 1060.66      40 1056.37      50 1054.23
      60 1052.64    89.9 1045.88    99.9 1043.97   119.9 1042.21   129.9 1041.66
   149.9 1042.59   159.9 1042.42   169.9 1041.94   179.9 1040.14   198.3 1039.29
  204.92 1037.99   207.6 1037.46   216.8  1038.3     226 1041.71   235.3 1043.42
   253.7  1043.3     321 1048.54   340.2  1049.7   397.9 1051.73   426.7 1052.04
   436.3 1053.12     446 1058.02   455.6 1061.48   465.2  1064.5   474.8 1066.27
#Mann= 3 , 0 , 0
       0     .05       0  204.92    .045       0   216.8     .05       0
Bank Sta=204.92,216.8
XS Rating Curve= 0 ,0
Exp/Cntr=0.3,0.1

Type RM Length L Ch R = 1 ,26977.5 ,238.9,212,180.5
XS GIS Cut Line= 4
     1799745.048      421629.963     1799872.652      421698.973
     1799916.923      421784.911     1800143.399      421881.916
#Sta/Elev= 30
       0 1069.86     9.7 1066.03    38.7 1058.85    48.4 1057.32      58 1053.73
    67.7 1052.43      87 1050.86    96.7 1049.05   116.1    1042   135.4 1041.64
   174.1 1040.18   183.7 1039.42  193.151036.975   203.1  1036.7  203.471036.781
   212.7 1038.86   222.4 1039.96   241.7 1040.53   251.6 1041.17   281.2    1041
     291  1041.7   310.7 1045.19   320.6 1046.64   350.2 1049.42   379.7 1050.77
   438.8 1052.18   448.7 1054.32   458.6 1057.51   478.3 1060.55   488.1 1062.81
#Mann= 3 , 0 , 0
       0     .05       0  193.15    .045       0  203.47     .05       0
Bank Sta=193.15,203.47
XS Rating Curve= 0 ,0
Exp/Cntr=0.3,0.1

Type RM Length L Ch R = 1 ,26765.5 ,353.2,357.4,361.4
XS GIS Cut Line= 4
     1799582.288      421911.213     1799873.955      421946.369
     1799998.955      421941.161     1800199.823      421895.805
#Sta/Elev= 30
       0 1065.28    29.4 1060.95    68.6 1061.14    78.3  1060.4    97.9  1057.6
   117.5 1055.57   127.3 1054.08   146.9 1049.07   166.5 1043.15   186.1 1039.75
   215.4 1039.53   254.6 1036.67   303.4 1036.39   341.9 1037.02   351.5 1036.72
  360.361035.409  367.391035.293   370.2 1035.29     390 1040.26   418.9 1040.78
   428.7 1043.96   438.5 1046.49   458.1 1050.43   467.9 1051.15     517  1052.6
   536.6 1055.15     566 1060.96   605.2 1071.72     615 1073.69   624.8 1075.01
#Mann= 3 , 0 , 0
       0     .05       0  360.36    .045       0  367.39     .05       0
Bank Sta=360.36,367.39
XS Rating Curve= 0 ,0
Exp/Cntr=0.3,0.1

Type RM Length L Ch R = 1 ,26408.1 ,166,160.6,154.3
XS GIS Cut Line= 6
     1799089.341      422164.519     1799476.494      422124.588
     1799672.674      422148.894     1799912.258      422233.963
      1800071.98      422272.157     1800413.994      422292.991
#Sta/Elev= 30
       0 1079.94      10 1083.81      20  1085.6    29.9 1084.78    39.9 1081.61
   119.8 1050.64   139.7 1044.05   229.5  1044.2   329.3 1042.98   349.3 1044.52
   418.9 1043.54   448.5 1040.08   458.4 1043.05   468.3 1044.35   527.6 1044.37
   586.9  1040.3   665.1 1040.77   860.4 1037.45   879.8  1036.2   908.8 1030.59
   928.1 1029.45   930.2 1029.47   945.2  1030.1  1005.4 1038.97  1034.7 1038.65
  1044.5 1040.26  1064.1 1041.55  1191.4 1047.97  1279.5 1051.15    1348 1060.92
#Mann= 3 , 0 , 0
       0     .07       0   930.2    .045       0   945.2     .08       0
Bank Sta=930.2,945.2
XS Rating Curve= 0 ,0
Exp/Cntr=0.3,0.1

Type RM Length L Ch R = 1 ,26247.6 ,444.6,442,433.7
XS GIS Cut Line= 4
      1799637.54      422433.999     1799965.231      422399.277
     1800088.929      422394.937     1800412.279      422377.576
#Sta/Elev= 30
       0 1096.48      30 1096.68    39.9 1096.09    69.9 1090.93   109.8 1086.48
   129.8 1082.45   149.8 1077.63   179.7 1069.28   189.7 1064.69   209.7  1047.5
   229.7 1033.86   239.6 1030.91   329.5 1031.82   348.6 1030.16   386.6 1028.94
  399.641027.686   405.7 1027.22   410.3 1027.71   415.2 1028.24   424.7 1030.72
   434.3 1032.45   453.3 1033.66   472.9  1038.6   492.6 1038.42   502.4 1039.51
     522 1039.54   649.6 1043.71     679 1046.25     728 1052.91   777.1 1057.98
#Mann= 3 , 0 , 0
       0      .1       0  399.64    .045       0   410.3      .1       0
#XS Ineff= 2 , 0
          328.82 1031.79
Permanent Ineff=
       F       F
Bank Sta=399.64,410.3
XS Rating Curve= 0 ,0
Exp/Cntr=0.3,0.1

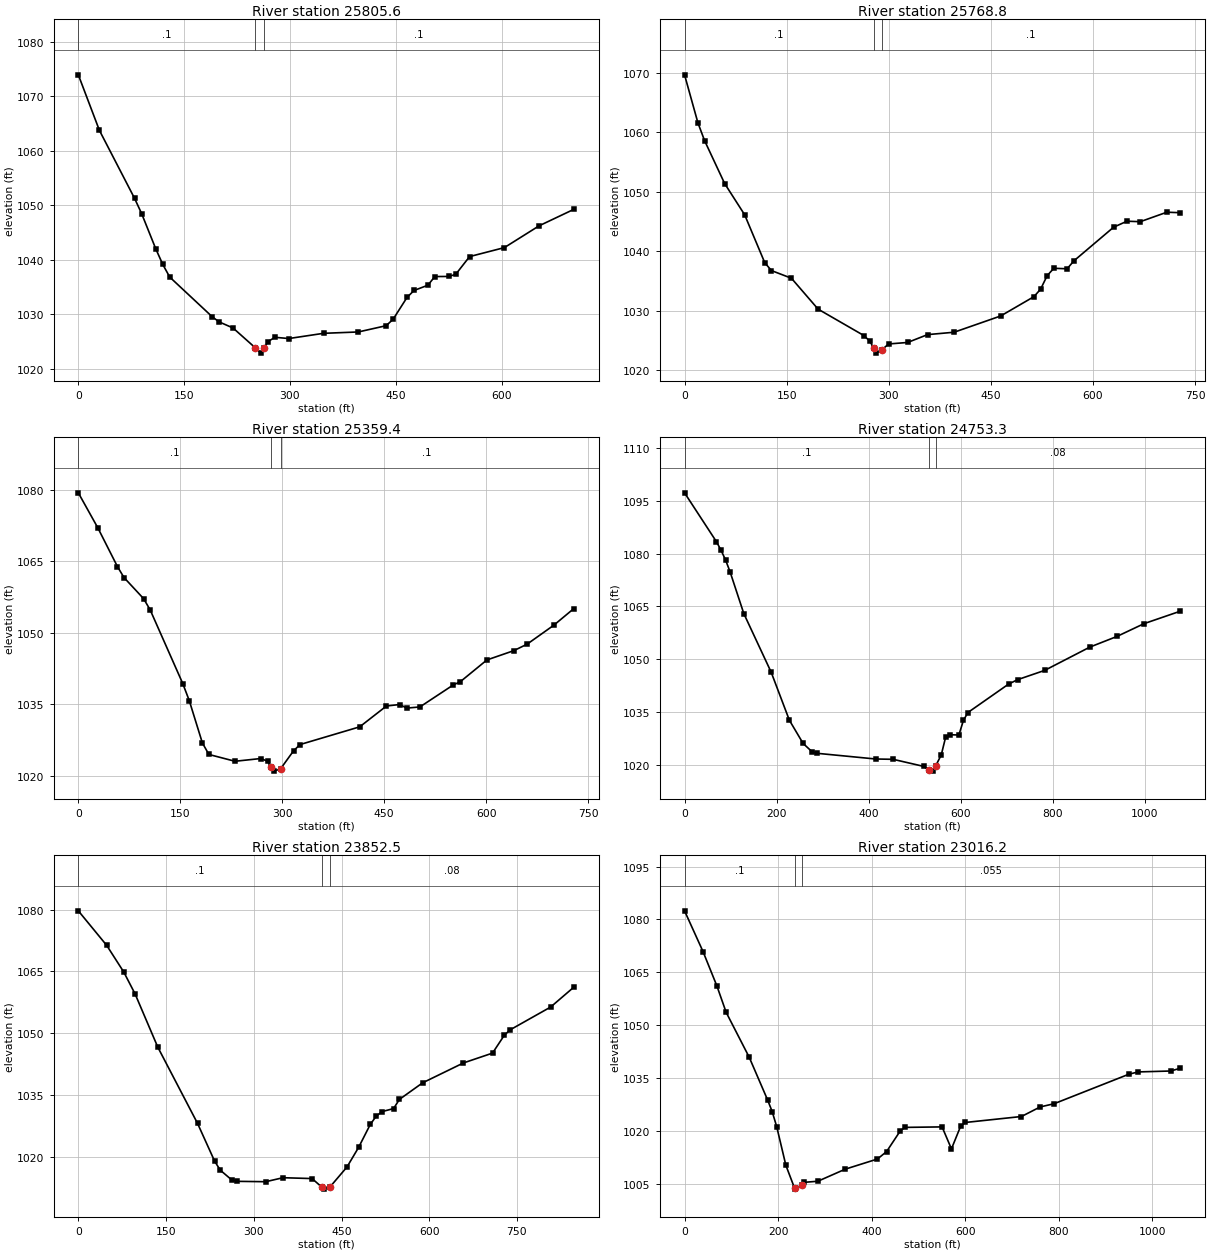
Type RM Length L Ch R = 1 ,25805.6 ,36.4,36.8,54.9
XS GIS Cut Line= 4
     1799739.536      422809.433     1799948.955      422810.518
      1800027.08      422798.582     1800430.725      422706.352
#Sta/Elev= 30
       0 1073.98    29.9 1063.77    79.8 1051.26    89.8 1048.46   109.7 1042.03
   119.7 1039.14   129.6 1036.81   189.5 1029.56   199.4 1028.59   219.3 1027.46
   251.1 1023.79   258.8 1022.84  263.161023.766   268.7 1024.94   278.6 1025.75
   298.3 1025.52   347.6 1026.48   396.9 1026.73   436.3 1027.88   446.2 1029.06
   465.9 1033.07   475.8 1034.35   495.5 1035.32   505.3 1036.91     525 1036.93
   534.9 1037.31   554.6 1040.58   603.9 1042.23   653.2 1046.24   702.5 1049.27
#Mann= 3 , 0 , 0
       0      .1       0   251.1    .045       0  263.16      .1       0
Bank Sta=251.1,263.16
XS Rating Curve= 0 ,0
Exp/Cntr=0.3,0.1

Type RM Length L Ch R = 1 ,25768.8 ,412.7,409.4,385
XS GIS Cut Line= 4
      1799725.43       422836.56     1799970.656       422843.07
     1800042.271      422831.135     1800442.661      422742.159
#Sta/Elev= 30
       0 1069.61    19.6 1061.56    29.4 1058.56    58.9 1051.35    88.3  1046.1
   117.8 1038.06   127.6 1036.73     157 1035.44   196.2 1030.25   263.5 1025.81
   272.5 1024.83  277.711023.704   281.6 1022.86   289.5 1023.38   299.8  1024.4
   327.7 1024.65     357 1025.97     396 1026.37   464.4  1029.1   513.2 1032.34
     523 1033.59   532.8 1035.89   542.5 1037.11   562.1 1037.03   571.8 1038.34
   630.4 1044.02     650 1045.02   669.5 1044.94   708.5 1046.53   728.1 1046.45
#Mann= 3 , 0 , 0
       0      .1       0  277.71    .045       0   289.5      .1       0
Bank Sta=277.71,289.5
XS Rating Curve= 0 ,0
Exp/Cntr=0.3,0.1

Type RM Length L Ch R = 1 ,25359.4 ,605.5,606.1,599.1
XS GIS Cut Line= 4
     1799928.338      423140.379     1800141.012      423051.404
     1800257.114      423006.916     1800604.336      422866.942
#Sta/Elev= 30
       0 1079.38    28.8    1072    57.6 1063.88    67.2 1061.59    96.1 1057.15
   105.7  1054.8   153.7 1039.32   163.3 1035.72   182.5 1026.87   192.1 1024.44
   230.5 1023.01   268.8 1023.59   278.4    1023   283.9 1021.81   287.9 1020.94
   297.5 1021.41   316.6 1025.19   326.2 1026.52     414 1030.24   453.4 1034.62
   473.1 1034.93     483 1034.17   502.6 1034.42   551.9 1039.06   561.8 1039.69
   601.2 1044.29   640.6 1046.23   660.3  1047.6   699.7 1051.59   729.2 1055.09
#Mann= 3 , 0 , 0
       0      .1       0   283.9    .045       0   297.5      .1       0
Bank Sta=283.9,297.5
XS Rating Curve= 0 ,0
Exp/Cntr=0.3,0.1

Type RM Length L Ch R = 1 ,24753.3 ,890.6,900.8,912.2
XS GIS Cut Line= 4
     1799982.176      423519.807     1800344.589      423359.216
     1800514.945      423274.798     1801004.311      423237.688
#Sta/Elev= 30
       0  1097.3    69.4 1083.38    79.3 1080.96    89.2 1078.18    99.1 1074.77
   128.8 1062.95   188.3 1046.26   227.9 1032.59   257.7    1026   277.5 1023.59
   287.4  1023.2   415.4 1021.57   453.4 1021.48     520 1019.46   530.5 1018.43
     539 1018.12   545.5 1019.52     558 1022.74   567.5 1027.78     577 1028.47
   596.3  1028.4   606.2 1032.55     616  1034.8   704.3 1042.88   723.9 1044.14
   782.8 1046.78     881 1053.41   939.9 1056.44   998.8 1060.08  1077.3 1063.61
#Mann= 3 , 0 , 0
       0      .1       0   530.5    .045       0   545.5     .08       0
Bank Sta=530.5,545.5
XS Rating Curve= 0 ,0
Exp/Cntr=0.3,0.1

Type RM Length L Ch R = 1 ,23852.5 ,825.6,836.3,842.3
XS GIS Cut Line= 3
     1800155.353      424083.609     1800485.214      424071.456
     1801002.575       424069.72
#Sta/Elev= 30
       0  1079.7    48.5 1071.32    77.7 1064.85    97.1 1059.53   135.9 1046.62
   203.9 1028.11     233 1018.98   242.7 1016.78   262.1 1014.44   271.8 1014.07
   320.4 1013.98     350 1014.95   399.7 1014.74   415.8 1012.73   419.6 1012.18
   430.8 1012.79   459.4 1017.56   479.3 1022.32   499.2 1027.88   509.2 1029.85
   519.1 1030.98     539 1031.72     549 1033.95   588.8 1037.98   658.4 1042.79
   708.2 1045.18   728.1 1049.46     738  1050.8   807.6 1056.36   847.4  1061.2
#Mann= 3 , 0 , 0
       0      .1       0   415.8    .045       0   430.8     .08       0
Bank Sta=415.8,430.8
XS Rating Curve= 0 ,0
Exp/Cntr=0.3,0.1

Type RM Length L Ch R = 1 ,23016.2 ,251.5,255.6,258.9
XS GIS Cut Line= 5
     1800220.768       424686.98     1800366.601      424747.743
     1800531.532      424832.813      1800684.31      424900.521
     1801229.449      424836.285
#Sta/Elev= 30
       0 1082.46    39.5 1070.89    69.1 1061.15    88.9 1053.65   138.2  1040.9
   177.5 1028.78   187.3 1025.47     197 1021.19   216.6 1010.21   235.3 1003.68
   236.1 1003.44   250.3 1004.63   255.7 1005.37     285 1005.68   343.6 1009.11
   412.4 1011.99     432 1014.11   461.5 1020.03   471.4 1020.97   550.6 1021.11
   570.6 1014.86   590.5 1021.37   600.5 1022.37   720.3 1024.06   760.2 1026.77
   790.1 1027.69   949.8 1036.06   969.8 1036.72  1039.6 1036.98  1059.6 1037.76
#Mann= 3 , 0 , 0
       0      .1       0   235.3    .045       0   250.3    .055       0
Bank Sta=235.3,250.3
XS Rating Curve= 0 ,0
Exp/Cntr=0.3,0.1

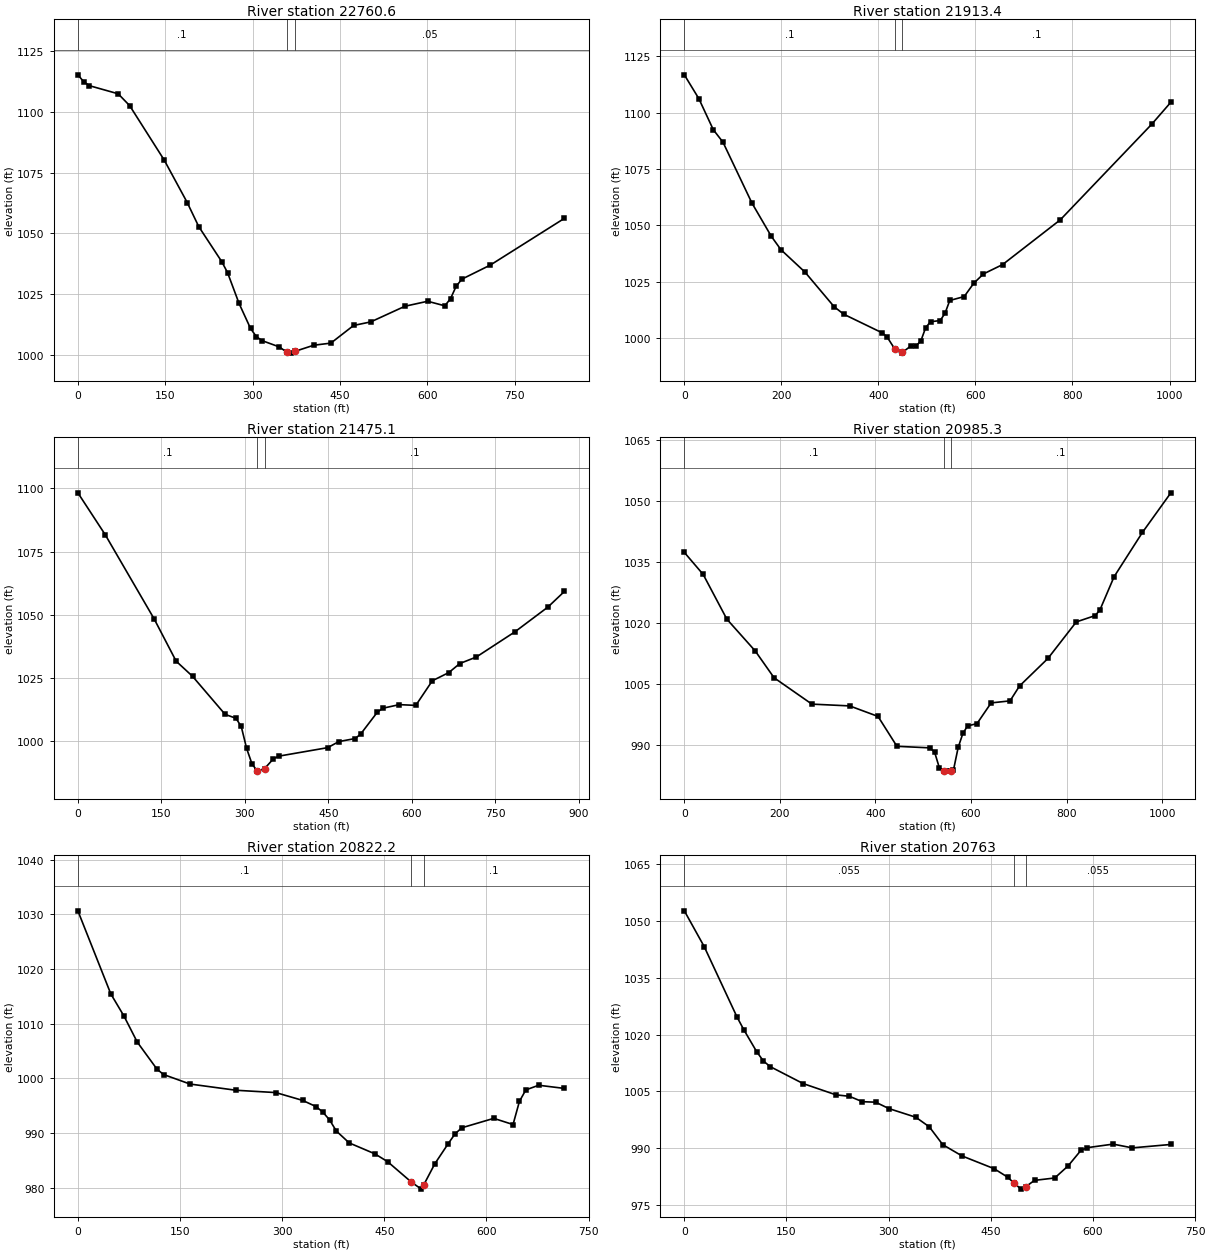
Type RM Length L Ch R = 1 ,22760.6 ,843.9,847.3,849.7
XS GIS Cut Line= 3
     1800042.506      424855.744     1800392.495      425017.543
     1800806.394      425194.286
#Sta/Elev= 30
       0 1115.16     9.9 1112.37    19.8  1110.7    69.2 1107.37      89 1102.48
   148.3 1080.14   187.8  1062.7   207.6 1052.81   247.2 1038.37     257 1033.94
   276.8 1021.26   296.6 1010.94   306.5 1007.62   316.4 1005.95     346 1003.37
   358.4 1001.29   365.8 1000.82   373.4 1001.59   405.2 1004.07   434.5 1004.93
   473.6 1012.19     503 1013.65   561.7 1020.08   600.8 1022.13   630.2 1020.26
     640 1023.19   649.7 1028.28   659.5 1031.21   708.4    1037   835.6 1056.19
#Mann= 3 , 0 , 0
       0      .1       0   358.4    .045       0   373.4     .05       0
Bank Sta=358.4,373.4
XS Rating Curve= 0 ,0
Exp/Cntr=0.3,0.1

Type RM Length L Ch R = 1 ,21913.4 ,430.6,438.2,445.4
XS GIS Cut Line= 3
     1799802.922       425547.15      1800199.63      425795.082
     1800650.144      426083.609
#Sta/Elev= 30
       0 1116.81    29.9 1106.25    59.7 1092.46    79.6 1086.95   139.4  1059.9
   179.2  1045.2   199.1 1039.24   248.8 1029.27   308.6 1013.98   328.5 1010.62
   408.1 1002.33     418 1000.48   434.4  994.99   447.9  993.36   449.4  993.69
   467.8  996.68   477.7  996.54   487.6  998.85   497.5 1004.68   507.4 1007.29
   527.2  1007.8   537.2 1010.96   547.1 1016.72   576.8 1018.44   596.6 1024.36
   616.4 1028.48     656 1032.64   774.9 1052.49   963.2 1094.86  1002.8 1104.65
#Mann= 3 , 0 , 0
       0      .1       0   434.4    .045       0   449.4      .1       0
Bank Sta=434.4,449.4
XS Rating Curve= 0 ,0
Exp/Cntr=0.3,0.1

Type RM Length L Ch R = 1 ,21475.1 ,505.6,489.8,473.9
XS GIS Cut Line= 4
     1799629.188      425765.973     1799785.438      425967.362
     1799875.716      426080.209     1800266.341      426349.306
#Sta/Elev= 30
       0  1098.2      49  1081.7   137.2 1048.31   176.5 1031.69   205.9 1025.72
   264.5 1010.66   283.8 1009.15   293.4 1005.92   303.1   997.2   312.7  991.12
   321.9988.3696   322.3  988.25  335.38989.2686   351.2  993.11   360.9  994.17
   448.8  997.53   468.6  999.92   498.2 1001.13   508.1 1002.95   537.8 1011.52
   547.6 1013.09   577.3 1014.52   606.9 1014.22   636.6 1023.95   666.2 1027.18
     686 1030.76   715.6 1033.33   784.8 1043.26   844.1 1053.05   873.8 1059.23
#Mann= 3 , 0 , 0
       0      .1       0   321.9    .045       0  335.38      .1       0
Bank Sta=321.9,335.38
XS Rating Curve= 0 ,0
Exp/Cntr=0.3,0.1

Type RM Length L Ch R = 1 ,20985.3 ,140.4,163.1,182.2
XS GIS Cut Line= 4
     1799430.092      426045.414     1799719.249      426446.311
     1799854.666      426471.919     1800237.384      426521.977
#Sta/Elev= 30
       0 1037.32    39.5 1031.88      89 1020.88   148.3 1013.06   187.8 1006.45
   266.9  999.96     346  999.52   405.3  996.93   444.9  989.57     514  989.19
   523.8   988.1   533.7  984.26   543.3  983.58   553.4  983.46   558.3  983.59
   563.2  983.72     573  989.28   582.9  992.75   592.7  994.59   612.4  995.16
     642 1000.26   681.6 1000.76   701.4 1004.42   760.8  1011.2   820.2  1020.2
   859.7 1021.76   869.6 1023.14   899.3 1031.33   958.7 1042.26  1018.1 1051.99
#Mann= 3 , 0 , 0
       0      .1       0   543.3    .045       0   558.3      .1       0
Bank Sta=543.3,558.3
XS Rating Curve= 0 ,0
Exp/Cntr=0.3,0.1

Type RM Length L Ch R = 1 ,20822.2 ,64.5,59.2,57.9
XS GIS Cut Line= 6
     1799341.334      426401.281     1799631.264      426479.406
     1799700.709        426517.6     1799737.167      426583.572
     1799804.875      426668.642     1799928.139      426755.447
#Sta/Elev= 30
       0 1030.64    48.4 1015.43    67.8 1011.36    87.2 1006.62   116.2 1001.66
   125.9 1000.68   164.7  998.94   232.5   997.8   290.6  997.38     330  995.95
   349.8  994.81   359.7   993.8   369.6  992.38   379.5  990.35   398.4  988.17
   436.1  986.17   454.9  984.73  489.59981.0107   504.3  979.71   508.1  980.54
   524.1  984.34   543.9  988.05   553.7   989.8   563.6  990.93   610.7  992.66
     639  991.53   648.4  995.78   657.8  997.87   676.7  998.72   714.4  998.14
#Mann= 3 , 0 , 0
       0      .1       0  489.59    .045       0   508.1      .1       0
Bank Sta=489.59,508.1
XS Rating Curve= 0 ,0
Exp/Cntr=0.3,0.1

Type RM Length L Ch R = 1 ,20763   ,297.2,278,258.4
XS GIS Cut Line= 6
     1799325.709      426462.045     1799615.639       426540.17
     1799685.084      426578.364     1799721.542      426644.336
      1799789.25      426729.406     1799912.514      426816.211
#Sta/Elev= 30
       0 1052.65    29.1 1043.24    77.5 1024.59    87.2 1021.33   106.6 1015.39
   116.2 1013.03   125.9 1011.58   174.4 1007.09   222.8 1004.11   242.2 1003.74
   261.5 1002.31   280.9 1002.18   300.3  1000.5   339.9  998.21   359.7  995.68
   379.5  990.97   407.8     988   454.9  984.64   474.7  982.41   484.6  980.77
   494.4  979.25   501.4   979.9   514.2  981.56   543.9  982.19   563.6  985.39
   582.5  989.51   591.9  990.19   629.6  991.12   657.8  990.13   714.4  991.03
#Mann= 3 , 0 , 0
       0    .055       0   484.6    .045       0   501.4    .055       0
Bank Sta=484.6,501.4
XS Rating Curve= 0 ,0
Exp/Cntr=0.3,0.1

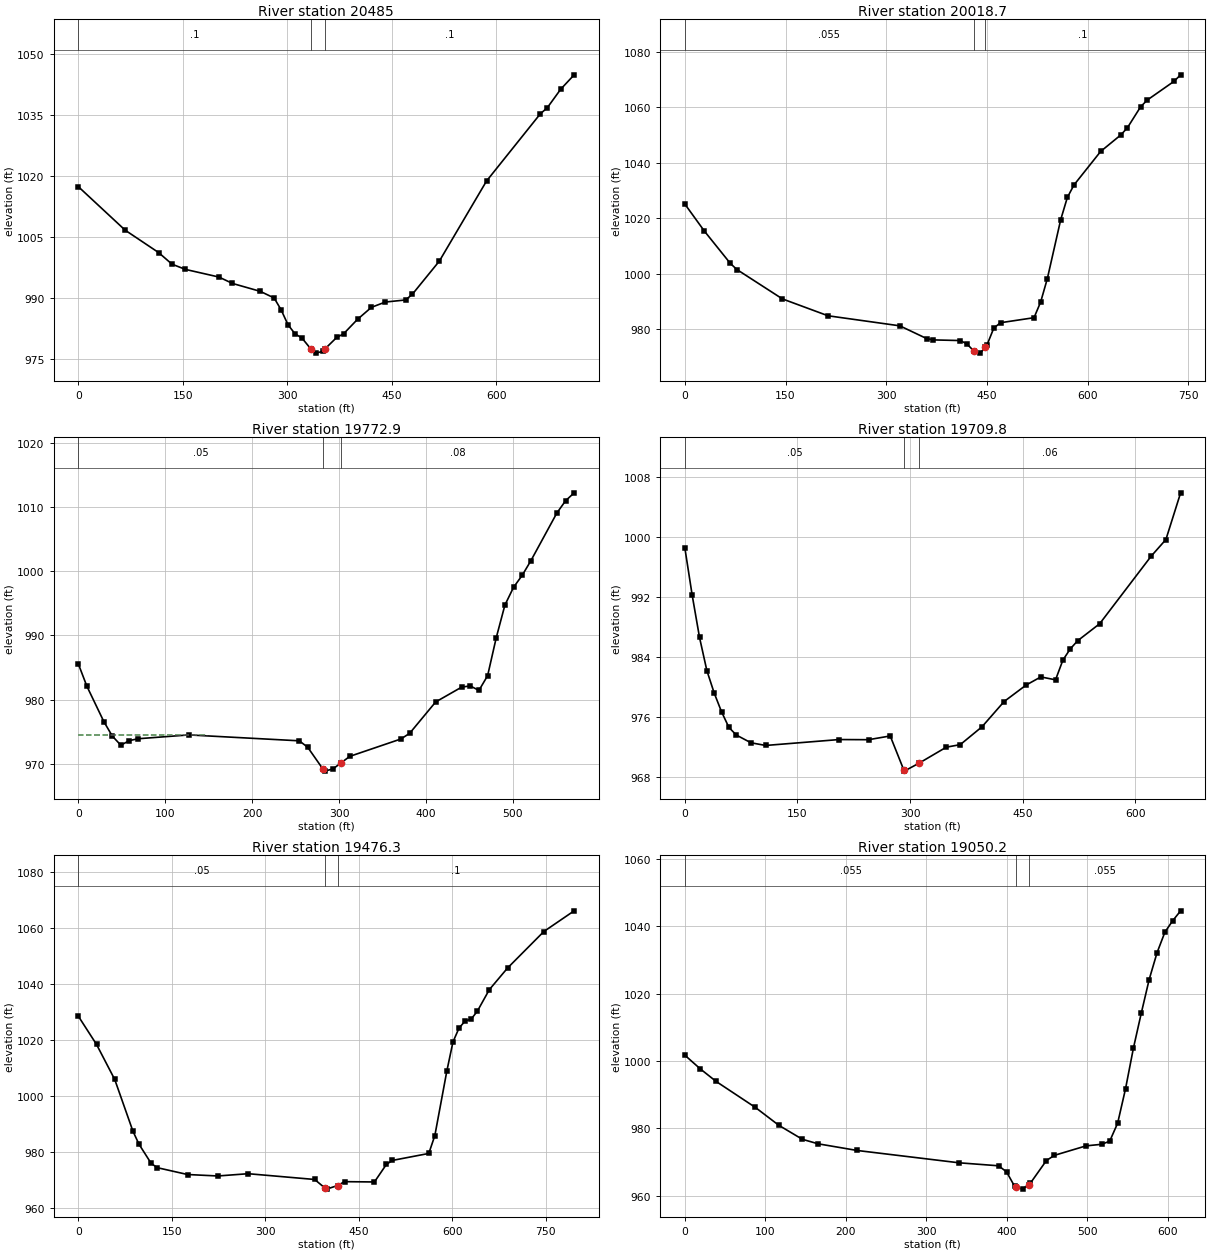
Type RM Length L Ch R = 1 ,20485   ,455.7,466.3,477
XS GIS Cut Line= 4
     1799424.667      426911.697     1799634.737      426934.267
     1799872.584      426958.572     1800079.181      427118.295
#Sta/Elev= 30
       0 1017.38    67.2 1006.65   115.2 1001.13   134.4  998.27   153.7  996.98
   201.7   995.1   221.2  993.52   261.1  991.57     281  989.93     291  987.01
   300.9  983.33   310.9   981.1   320.9  980.06   333.5977.3973   340.8  976.34
   350.8  976.78  353.75977.3517   370.7   980.2   380.6   981.1   400.6  984.67
   420.5  987.62   440.4  988.93   469.7  989.45   479.4  990.87   518.1  999.04
   585.8 1018.78   663.1 1035.37   672.8  1036.8   692.2  1041.4   711.5 1044.95
#Mann= 3 , 0 , 0
       0      .1       0   333.5    .045       0  353.75      .1       0
Bank Sta=333.5,353.75
XS Rating Curve= 0 ,0
Exp/Cntr=0.3,0.1

Type RM Length L Ch R = 1 ,20018.7 ,250.3,245.8,241.3
XS GIS Cut Line= 4
     1799311.386      427159.021     1799580.917      427312.667
     1799739.771      427416.833     1799954.615      427519.698
#Sta/Elev= 30
       0 1025.16    29.1 1015.42    67.9 1003.74    77.6 1001.56   145.4  990.98
   213.3  984.91   320.2  981.29   360.2   976.7   370.2  976.22   410.2  975.99
   420.2  974.78   430.2  972.26   440.2  971.46   447.4  973.63   450.2  974.48
   460.2   980.5   470.2  982.41   520.1  984.22     530  989.91   539.9  998.28
   559.8  1019.5   569.7 1027.51   579.6 1032.02   619.3 1044.08   649.1 1049.98
     659 1052.55   678.9 1060.19   688.8  1062.6   728.5 1069.32   738.4 1071.67
#Mann= 3 , 0 , 0
       0    .055       0   430.2    .045       0   447.4      .1       0
Bank Sta=430.2,447.4
XS Rating Curve= 0 ,0
Exp/Cntr=0.3,0.1

Type RM Length L Ch R = 1 ,19772.9 ,63.1,63.2,63.2
XS GIS Cut Line= 4
     1799234.563      427414.229     1799455.917      427518.396
     1799544.459      427557.458        1799758.      427640.792
#Sta/Elev= 30
       0  985.56     9.8  982.09    29.4  976.56    39.1  974.32    48.9   972.9
    58.7  973.61    68.5   973.9   127.2   974.5   254.3  973.58     264  972.57
  281.36969.2091   283.4  968.86     293   969.2   302.7  970.18   312.4  971.16
   371.3  973.87   381.3  974.75   411.2  979.63   441.1  981.94     451  982.13
     461  981.43     471  983.72   480.9  989.62   490.9  994.72   500.9   997.5
   510.8  999.35   520.8 1001.63   550.7 1009.06   560.7 1010.96   570.6  1012.2
#Mann= 3 , 0 , 0
       0     .05       0  281.36    .045       0   302.7     .08       0
#XS Ineff= 2 , 0
          148.48  974.45
Permanent Ineff=
       F       F
Bank Sta=281.36,302.7
XS Rating Curve= 0 ,0
Exp/Cntr=0.3,0.1

Type RM Length L Ch R = 1 ,19709.8 ,234.7,233.5,232.2
XS GIS Cut Line= 4
     1799170.761      427467.615     1799416.855      427563.969
     1799519.719       427608.24     1799784.042      427712.406
#Sta/Elev= 30
       0  998.62     9.8  992.28    19.6  986.62    29.4  982.18    39.2  979.17
    48.9  976.69    58.7   974.6    68.5  973.58    88.1  972.54   107.7  972.18
   205.6  972.97   244.7  972.95   273.6  973.45   291.8968.8737   292.3  968.75
   312.3  969.83   348.3  971.95   366.9  972.29   395.9  974.68   425.3  978.05
   454.6  980.25   474.2  981.34   493.8  980.95   503.6  983.59   513.4  985.08
   523.2  986.17   552.6  988.45   621.2  997.48   640.8   999.7   660.4 1005.94
#Mann= 3 , 0 , 0
       0     .05       0   291.8    .045       0   312.3     .06       0
#XS Ineff= 2 , 0
          272.88   973.4
Permanent Ineff=
       F       F
Bank Sta=291.8,312.3
XS Rating Curve= 0 ,0
Exp/Cntr=0.3,0.1

Type RM Length L Ch R = 1 ,19476.3 ,419.7,426,430.9
XS GIS Cut Line= 4
     1798991.073         427646.     1799317.896      427772.302
     1799453.313      427820.479     1799728.052      427944.177
#Sta/Elev= 30
       0 1028.56    29.2 1018.46    58.4 1005.94    87.6  987.45    97.3  982.81
   116.8  975.98   126.5  974.43   175.2  971.98   223.8  971.46   272.5  972.27
   379.1  970.21  396.25967.0397   398.3  966.76   415.8  968.04     427  969.43
     475  969.32   494.1  975.57   503.8  977.02   562.2  979.51   571.9  985.89
   591.3 1009.13     601 1019.37   610.7 1024.31   620.5 1026.84   630.2 1027.53
   639.9 1030.27   659.3 1038.04   688.5 1045.76   746.8 1058.82   795.4 1066.21
#Mann= 3 , 0 , 0
       0     .05       0  396.25    .045       0   415.8      .1       0
#XS Ineff= 2 , 0
          271.97  972.22
Permanent Ineff=
       F       F
Bank Sta=396.25,415.8
XS Rating Curve= 0 ,0
Exp/Cntr=0.3,0.1

Type RM Length L Ch R = 1 ,19050.2 ,43.5,43.4,43.3
XS GIS Cut Line= 4
     1798848.278      427951.122      1799162.08      428128.205
     1799267.549      428182.892     1799393.851      428236.278
#Sta/Elev= 30
       0 1001.74    19.5  997.61      39  993.92    87.6  986.23   116.9   980.9
   146.1  976.75   165.6  975.41   214.2  973.43   340.8  969.77     390  968.88
   399.9  967.07   409.8  962.81   412.2   962.6   419.7  961.95   427.2  963.32
   429.6  963.76   449.4  970.44   459.3  971.98   498.7   974.8   518.3  975.27
   528.1  976.21   537.9  981.52   547.7  991.72   557.5  1003.8   567.3 1014.21
   577.1  1024.2   586.9 1032.16   596.7 1038.29   606.4 1041.68   616.2  1044.6
#Mann= 3 , 0 , 0
       0    .055       0   412.2    .045       0   427.2    .055       0
Bank Sta=412.2,427.2
XS Rating Curve= 0 ,0
Exp/Cntr=0.3,0.1

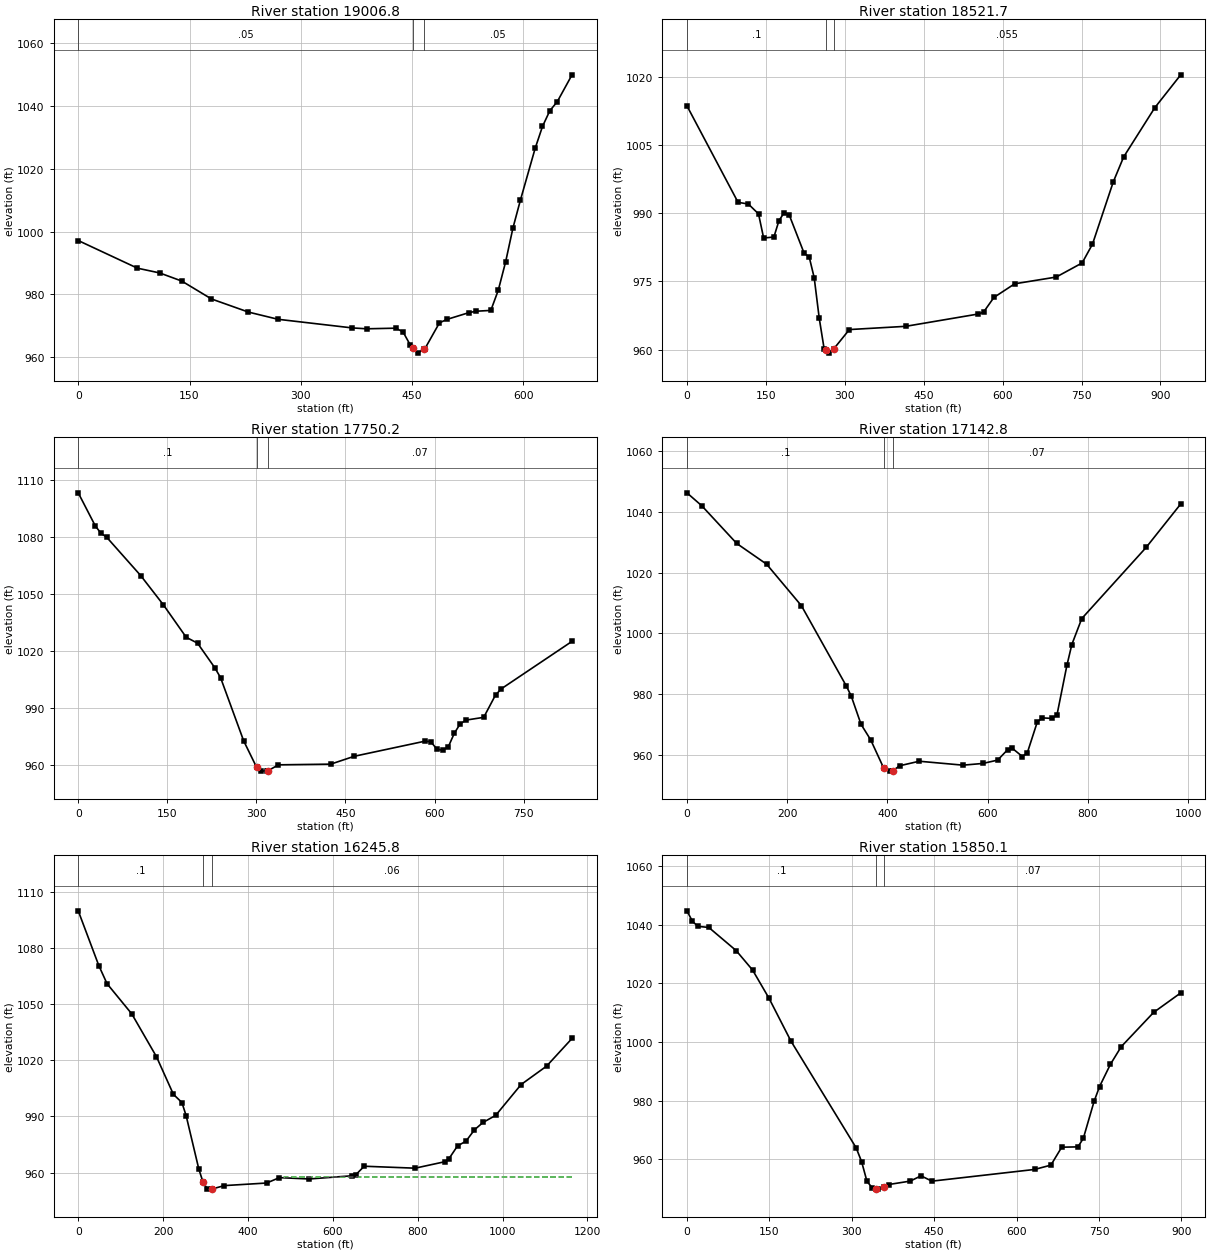
Type RM Length L Ch R = 1 ,19006.8 ,473.6,485.1,494.9
XS GIS Cut Line= 4
     1798799.667      427978.031     1799122.584      428156.417
      1799244.98      428218.917     1799385.605      428293.136
#Sta/Elev= 30
       0  997.18    79.8  988.37   109.7  986.86   139.6  984.26   179.5  978.57
   229.3  974.39   269.2  972.09   368.9  969.35   388.6  969.06   427.8  969.26
   437.6   968.1   447.4  963.91   450.6  963.07   457.3  961.31   465.6  962.49
   467.1   962.7   486.7  970.94   496.5  972.03   526.2  974.19   536.2  974.66
     556  974.92     566  981.34   575.9  990.36   585.8 1001.19   595.8 1010.01
   615.7 1026.54   625.6 1033.53   635.5 1038.54   645.5 1041.41   665.4 1049.97
#Mann= 3 , 0 , 0
       0     .05       0   450.6    .045       0   465.6     .05       0
Bank Sta=450.6,465.6
XS Rating Curve= 0 ,0
Exp/Cntr=0.3,0.1

Type RM Length L Ch R = 1 ,18521.7 ,774.6,771.5,768.3
XS GIS Cut Line= 4
     1798708.521      428062.667     1798836.125      428182.458
     1798958.521      428316.573     1799235.865      428828.292
#Sta/Elev= 30
       0 1013.58    97.2  992.36   116.7     992   136.1  989.82   145.8  984.52
   165.3  984.74     175  988.36   184.6  990.04   194.1  989.69   222.8  981.17
   232.4  980.36   241.9  975.81   251.5  966.88     261  960.02   263.7   959.8
   270.6  959.22   278.7   960.1   308.8   964.4   415.8  965.11   553.9  967.82
   563.8  968.23   583.5  971.46     623  974.46   701.9  975.94   751.2  979.04
   770.9  983.18   810.4  996.86   830.1 1002.34   889.3 1013.16   938.6 1020.39
#Mann= 3 , 0 , 0
       0      .1       0   263.7    .045       0   278.7    .055       0
Bank Sta=263.7,278.7
XS Rating Curve= 0 ,0
Exp/Cntr=0.3,0.1

Type RM Length L Ch R = 1 ,17750.2 ,607,607.3,603.9
XS GIS Cut Line= 4
     1798170.761      428573.083     1798328.313      428726.729
     1798479.355      428850.427     1798777.532      429140.792
#Sta/Elev= 30
       0 1103.07    28.7 1085.72    38.3 1081.81    47.8 1079.78   105.2  1059.6
   143.5 1044.19   181.8  1027.2   200.9  1024.1   229.8 1011.26   239.6 1006.04
   278.6  972.76   300.2     959   307.9  957.02   317.7  956.88  320.11957.1831
   337.2  960.19   425.2  960.55   464.8  964.68   583.8  972.61   593.7  972.34
   603.6  968.56   613.5  967.76   623.4   969.8   633.3  976.79   643.2  981.72
   653.1  983.69   682.8  985.14   702.7  996.88   712.6 1000.16   831.5 1025.05
#Mann= 3 , 0 , 0
       0      .1       0   300.2    .045       0  320.11     .07       0
Bank Sta=300.2,320.11
XS Rating Curve= 0 ,0
Exp/Cntr=0.3,0.1

Type RM Length L Ch R = 1 ,17142.8 ,861.2,897.1,880
XS GIS Cut Line= 4
     1797768.808      428902.337     1798005.353      429143.222
     1798144.242      429277.771     1798417.679      429640.184
#Sta/Elev= 30
       0 1046.19    29.8 1041.91    99.3 1029.56   158.9 1022.75   228.4  1009.1
   317.8  982.77   327.7  979.45   347.3  970.14   366.6  965.02   392.7  955.68
   405.3  954.76  410.56954.9123   424.6  956.53   463.3  958.01   550.7  956.72
   590.2  957.28   619.8  958.38   639.6  961.78   649.4  962.21   669.2  959.55
     679  960.78   698.8  970.87   708.6  972.26   728.4  972.07   738.2  973.26
     758  989.54   767.8  996.36   787.6 1004.88   915.9 1028.23     985 1042.53
#Mann= 3 , 0 , 0
       0      .1       0   392.7    .045       0  410.56     .07       0
#XS Ineff= 2 , 0
                          639.54          961.72
Permanent Ineff=
       F       F
Bank Sta=392.7,410.56
XS Rating Curve= 0 ,0
Exp/Cntr=0.3,0.1

Type RM Length L Ch R = 1 ,16245.8 ,394.2,395.7,397.4
XS GIS Cut Line= 4
     1797407.617       429496.55     1797562.044      429597.273
     1797835.482      429742.673      1798438.52      430033.471
#Sta/Elev= 30
       0 1099.69    48.5 1070.46    67.9 1060.79   126.2 1044.68   184.4 1021.82
   224.3 1001.74   244.3  997.38   254.3  990.33   284.3  961.73   294.3  954.74
   304.2  951.29   314.2  951.16   344.2  953.04   444.1  954.42   474.1   957.3
     544  956.58     644  958.26   653.9   958.8   673.9  963.38   793.8  962.34
   863.8  965.78   873.8  967.48   893.8  974.21   913.7  976.76   933.7  982.81
   953.7  986.73   983.7  990.53  1043.6 1006.98  1103.6  1016.8  1163.6 1031.58
#Mann= 3 , 0 , 0
       0      .1       0   294.3    .045       0   314.2     .06       0
#XS Ineff= 2 , 0
                          484.06          957.46
Permanent Ineff=
       F       F
Bank Sta=294.3,314.2
XS Rating Curve= 0 ,0
Exp/Cntr=0.3,0.1

Type RM Length L Ch R = 1 ,15850.1 ,437.9,421.7,403.1
XS GIS Cut Line= 4
     1797199.797      429754.767     1797412.037      429884.976
     1797548.756       429981.33     1797940.683       430262.58
#Sta/Elev= 30
       0 1044.76      10 1041.19    19.9 1039.46    39.8 1039.09    89.6 1031.19
   119.5 1024.55   149.4 1014.92   189.2 1000.34     308  963.88   317.9  959.17
   327.7  952.42   337.6  950.16   343.7  949.93   347.4  949.79   358.7  950.36
   367.1  951.36   406.4  952.53   426.1  954.33   445.8  952.51   632.8  956.51
   662.4  957.98   682.1   964.1   711.6  964.21   721.4   967.1   741.1  979.78
     751  984.81   770.7  992.37   790.4   998.4   849.4  1010.1   898.7 1016.75
#Mann= 3 , 0 , 0
       0      .1       0   343.7    .045       0   358.7     .07       0
Bank Sta=343.7,358.7
XS Rating Curve= 0 ,0
Exp/Cntr=0.3,0.1