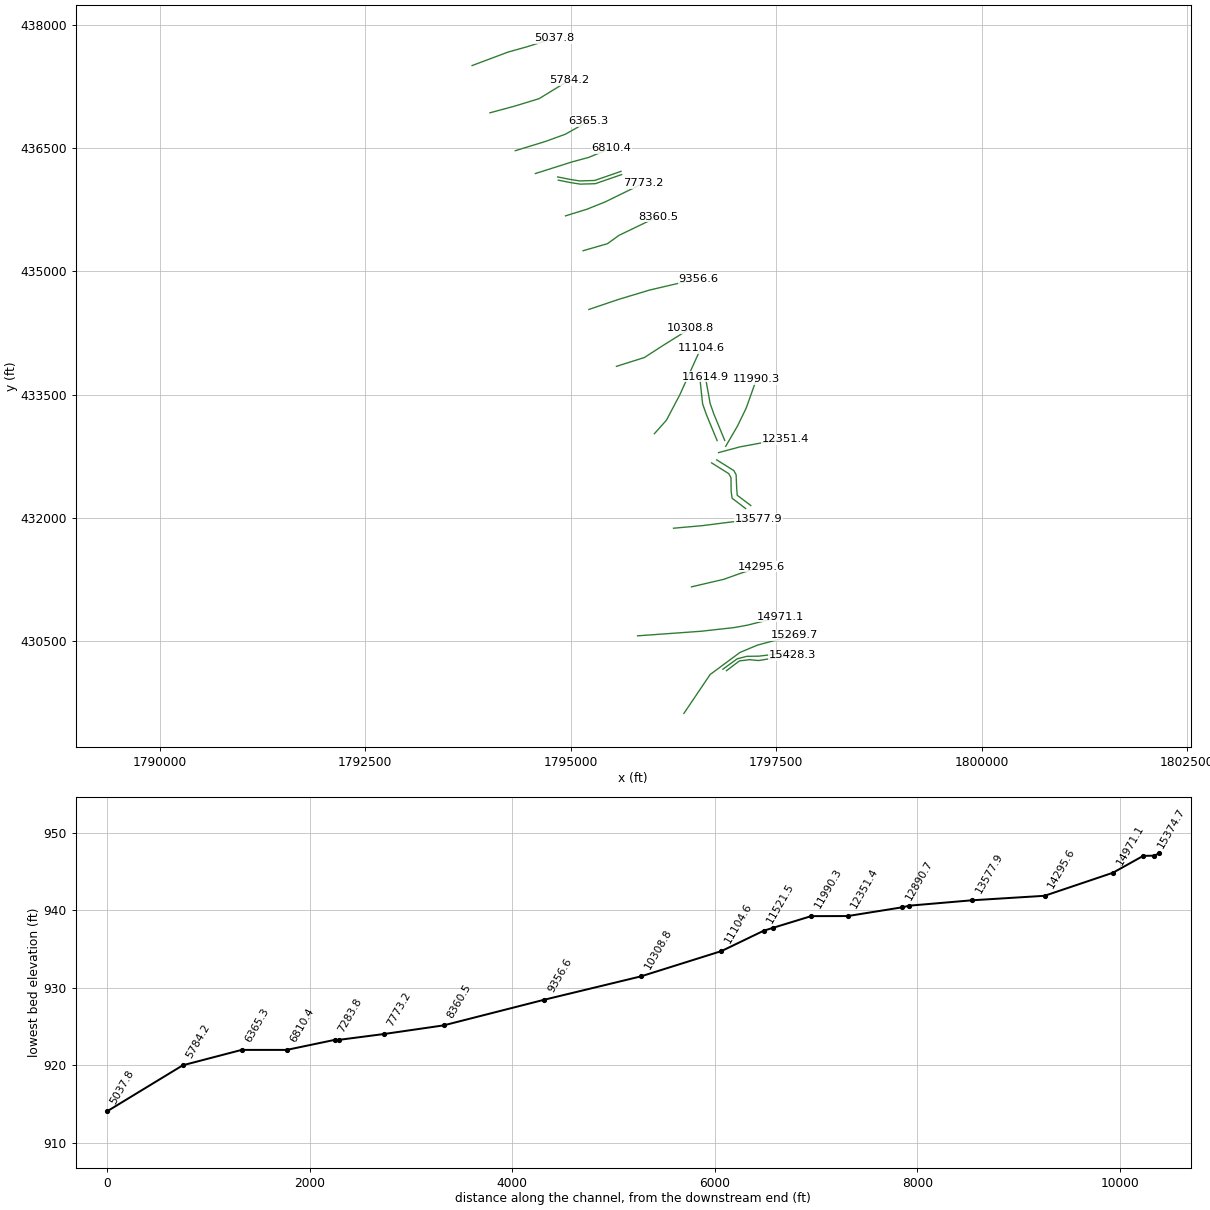
HEC-RAS study DollsRun.prj: DollsRun

--- DollsRun.g01 (geometry) --- (continued)

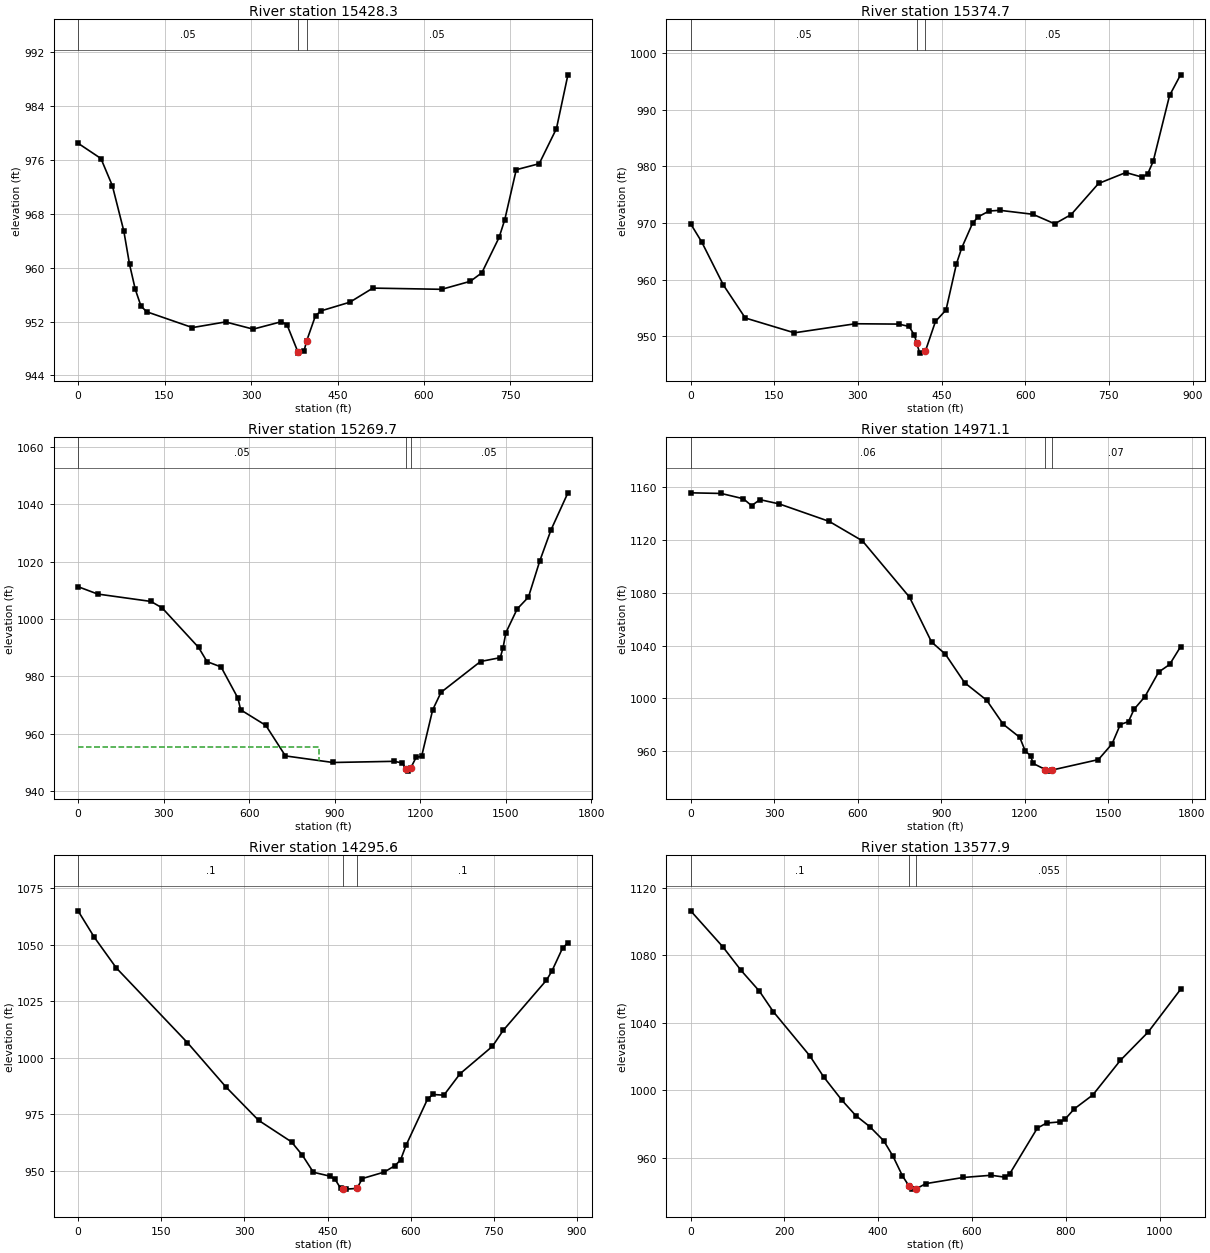
Type RM Length L Ch R = 1 ,15428.3 ,51.3,53.6,57.5
XS GIS Cut Line= 5
      1796895.11      430138.882     1797053.638      430258.131
     1797177.336      430272.237     1797285.735       430262.58
     1797698.495      430327.684
#Sta/Elev= 30
       0  978.46    39.7  976.19    59.5  972.16    79.4  965.43    89.3   960.5
    99.2   956.8   109.1   954.3     119  953.45   198.4   951.1   255.8  951.94
   303.7  950.87   352.6  951.97   362.4  951.52   381.5  947.45   382.2  947.31
   392.1  947.68   396.5  949.13   411.9  952.89   421.8  953.59   471.5  954.87
   511.3  956.96   630.7  956.78   680.4  957.97   700.3  959.23   730.2  964.47
   740.1  967.12     760  974.53   799.8  975.42   829.7  980.63   849.6  988.61
#Mann= 3 , 0 , 0
       0     .05       0   381.5    .045       0   396.5     .05       0
Bank Sta=381.5,396.5
XS Rating Curve= 0 ,0
Exp/Cntr=0.3,0.1

Type RM Length L Ch R = 1 ,15374.7 ,95.9,105,114.4
XS GIS Cut Line= 5
     1796852.141      430157.111      1797026.62      430283.413
     1797142.614       430313.47     1797293.547      430315.965
      1797682.87      430364.142
#Sta/Elev= 30
       0  969.86    19.6   966.7    58.7  959.05    97.9  953.23     186  950.61
   295.3  952.21     373  952.15   391.8  951.73   401.3  950.17   405.2  948.86
   410.7  947.02  421.06947.4159     439  952.62   457.9  954.64   476.7  962.83
   486.2  965.64   505.8  970.03   515.6   971.1   535.2  972.13   554.8  972.25
   613.7  971.55   652.9  969.87   682.3   971.5   731.4  976.99   780.4  978.93
   809.8  978.11   819.6   978.7   829.4  980.89   858.8  992.54   878.5  996.19
#Mann= 3 , 0 , 0
       0     .05       0   405.2    .045       0  421.06     .05       0
Bank Sta=405.2,421.06
XS Rating Curve= 0 ,0
Exp/Cntr=0.3,0.1

Type RM Length L Ch R = 1 ,15269.7 ,302.7,298.6,294.4
XS GIS Cut Line= 5
     1796377.539      429619.271     1796696.415      430092.109
     1797058.919      430360.381     1797272.714       430450.08
      1797721.68      430570.016
#Sta/Elev= 30
       0 1011.32    68.8 1008.75   255.7 1006.17     295 1003.91   422.8  990.12
   452.3  985.18   501.5  983.33   560.5  972.47   570.3  968.37   658.6  962.93
   727.2   952.3   893.8     950  1108.2  950.41  1137.2  949.84  1150.2  947.69
  1156.5  946.99  1166.2  948.03  1185.5  951.77  1204.8  952.15  1243.5  968.34
  1272.9  974.48  1411.3  985.22  1480.6  986.57  1490.4  990.07  1500.3  995.28
  1539.9 1003.55  1579.4 1007.69    1619 1020.26  1658.5 1031.12  1717.8 1044.05
#Mann= 3 , 0 , 0
       0     .05       0  1150.2    .045       0  1166.2     .05       0
#XS Ineff= 2 , 0
           845.2  955.39
Permanent Ineff=
       F       F
Bank Sta=1150.2,1166.2
XS Rating Curve= 0 ,0
Exp/Cntr=0.3,0.1

Type RM Length L Ch R = 1 ,14971.1 ,673.1,675.6,678.1
XS GIS Cut Line= 5
     1795813.303      430563.065     1796587.684      430618.817
     1796991.211      430663.766     1797152.922       430693.57
     1797553.964       430793.83
#Sta/Elev= 30
       0 1155.83   109.5 1155.36   189.1 1151.35     219 1146.08   248.8 1150.67
   318.5  1147.4   497.7 1134.18   617.1 1119.43   786.3 1076.74   865.5 1042.74
     915 1033.55   984.4 1011.85  1063.6  998.59    1123  980.37  1182.4  970.44
  1201.8  960.27  1221.1  956.47  1230.8  950.61  1274.4  946.03  1288.8  944.82
  1298.5  945.63    1465  953.56  1514.2  965.52  1543.7  980.14  1573.2  982.37
  1592.9  991.64  1632.3 1001.34  1681.5 1019.92  1720.9 1025.68  1760.2  1039.1
#Mann= 3 , 0 , 0
       0     .06       0  1274.4    .045       0  1298.5     .07       0
Bank Sta=1274.4,1298.5
XS Rating Curve= 0 ,0
Exp/Cntr=0.3,0.1

Type RM Length L Ch R = 1 ,14295.6 ,722.2,717.7,712.7
XS GIS Cut Line= 4
     1796469.437      431159.173     1796863.534      431251.187
     1797057.979      431320.631     1797316.659      431405.701
#Sta/Elev= 30
       0 1064.93    29.6 1053.14    69.1 1039.65   197.4  1006.6   266.5   987.1
   325.7  972.26     385  962.74   404.7  956.81   424.4  949.31   453.9  947.61
   463.7  946.12   473.5  942.25   478.6  942.04   483.4  941.85     503  942.16
   512.8  946.54   552.2  949.39   571.8  952.27   581.7  954.77   591.5  961.19
   630.6   981.8   640.4   983.7   659.8   983.4     689  992.88   747.3 1004.99
   766.8 1012.06   844.6  1034.2   854.3 1038.13   873.8 1048.43   883.5 1050.83
#Mann= 3 , 0 , 0
       0      .1       0   478.6    .045       0     503      .1       0
Bank Sta=478.6,503
XS Rating Curve= 0 ,0
Exp/Cntr=0.3,0.1

Type RM Length L Ch R = 1 ,13577.9 ,655,616.4,578.2
XS GIS Cut Line= 4
     1796250.687      431872.715     1796601.381      431903.965
      1796887.84      431940.423     1797288.881      431989.034
#Sta/Elev= 30
       0 1106.49    68.5 1085.15   107.6 1071.09   146.7 1058.76     176 1046.71
   254.3 1020.34   283.6 1007.93   322.7  994.01   352.1  984.95     382  978.37
   411.8  969.96   431.7   960.7   451.7  949.14   465.9  942.98   471.6  941.27
   481.5  941.53   501.4  944.53   581.1  948.18   640.8   949.5   670.4  948.36
   680.3  950.28   739.4  977.52   759.1   980.5   788.6  981.21   798.5  982.82
   818.2  988.92   857.6  997.16   916.7  1017.8   975.9 1034.57  1044.8 1059.85
#Mann= 3 , 0 , 0
       0      .1       0   465.9    .045       0   481.5    .055       0
Bank Sta=465.9,481.5
XS Rating Curve= 0 ,0
Exp/Cntr=0.3,0.1

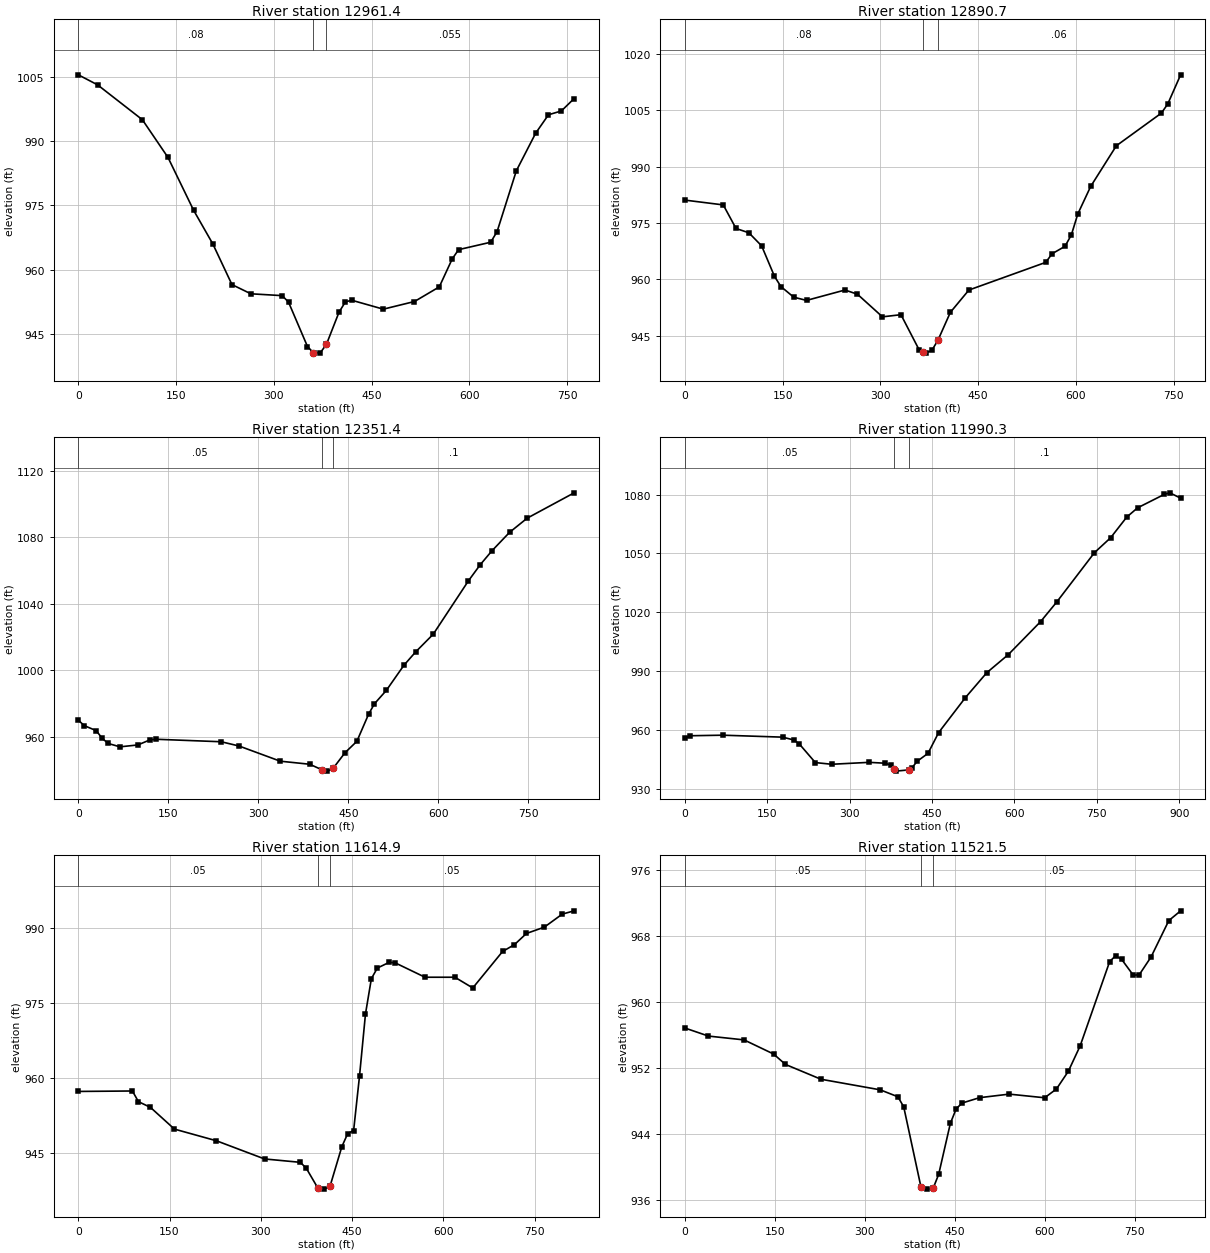
Type RM Length L Ch R = 1 ,12961.4 ,75.7,70.7,71.1
XS GIS Cut Line= 6
     1796714.229      432667.853     1796922.562      432537.645
      1796950.34      432487.298     1796952.076      432322.367
     1796964.229      432237.298     1797129.159      432112.298
#Sta/Elev= 30
       0  1005.4    29.5 1003.07    98.3  994.94   137.6  986.16   176.9  973.86
   206.4  966.02   235.8  956.54   264.8   954.4   312.9  953.97   322.6  952.46
   351.7  942.12   360.9  940.66   361.4  940.58   371.1   940.6   380.8  942.63
   400.2  950.15   409.9  952.51   419.6   952.9   468.1  950.82   515.9   952.6
     554  956.01   573.8  962.51   583.6  964.68   632.9  966.41   642.7  968.88
   672.3  983.07   701.9   991.8   721.6   996.1   741.3  996.98     761  999.88
#Mann= 3 , 0 , 0
       0     .08       0   360.9    .045       0   380.8    .055       0
Bank Sta=360.9,380.8
XS Rating Curve= 0 ,0
Exp/Cntr=0.3,0.1

Type RM Length L Ch R = 1 ,12890.7 ,493.6,539.3,579
XS GIS Cut Line= 6
     1796776.729      432704.312     1796985.062      432574.103
      1797012.84      432523.756     1797020.001        432353.4
     1797026.729      432273.756     1797191.659      432148.756
#Sta/Elev= 30
       0   981.1      59  979.82    78.6  973.54    98.3   972.4   117.9  968.91
   137.6   960.8   147.4  958.09   167.1  955.26   186.7   954.4   245.7  957.17
   264.8  956.05   303.2  950.03   331.6   950.6     360  941.07  364.86940.7081
   369.4  940.37     379  941.11   388.4  943.83   407.4  951.23   435.8  957.16
   553.6  964.52   563.5  966.83   583.2  968.79     593  971.85   602.9  977.42
   622.6  984.73     662  995.56     731 1004.24   740.8 1006.66   760.6 1014.44
#Mann= 3 , 0 , 0
       0     .08       0  364.86    .045       0   388.4     .06       0
Bank Sta=364.86,388.4
XS Rating Curve= 0 ,0
Exp/Cntr=0.3,0.1

Type RM Length L Ch R = 1 ,12351.4 ,339.7,361.2,382.6
XS GIS Cut Line= 4
     1796799.298      432792.853     1797057.979      432862.298
     1797318.395      432910.909     1797608.326      432956.048
#Sta/Elev= 30
       0   969.9     9.9  966.62    29.8   963.6    39.7  959.02    49.6   955.9
    69.4  953.86    99.2     955     119     958     129  958.43   238.1  956.92
   267.8  954.36   336.5  945.22   385.6  943.38   405.2  940.17     415  939.24
   424.6  940.94   444.4  950.34   464.1  957.17   483.7  973.53   493.5  979.82
   513.1  987.77   542.5 1002.94   562.1    1011   591.4 1021.66   650.1 1053.82
   669.7 1063.47   689.2 1071.85   718.6 1082.96   747.9 1091.48   826.2 1106.74
#Mann= 3 , 0 , 0
       0     .05       0   405.2    .045       0   424.6      .1       0
Bank Sta=405.2,424.6
XS Rating Curve= 0 ,0
Exp/Cntr=0.3,0.1

Type RM Length L Ch R = 1 ,11990.3 ,357.2,375.4,393.5
XS GIS Cut Line= 4
     1796886.104      432869.242     1797030.201      433117.506
     1797136.104      433336.256     1797261.104      433686.951
#Sta/Elev= 30
       0  955.95     9.9  957.24    69.3  957.52   178.2  956.52     198  955.11
   207.9  953.22   237.6  943.58   267.3  942.72   335.7   943.7   364.8  943.25
   374.6  942.31   381.1  940.25   384.3  939.23  407.19939.8488   413.4  940.95
   423.2   944.3   442.6  948.27     462  958.85   510.6  976.61   549.7  989.35
   588.9  998.57   647.7 1015.37     677 1025.33   745.6 1050.43     775 1058.01
   804.4 1068.54     824 1073.22     873 1080.13   882.8 1080.87   902.4 1078.16
#Mann= 3 , 0 , 0
       0     .05       0   381.1    .045       0  407.19      .1       0
Bank Sta=381.1,407.19
XS Rating Curve= 0 ,0
Exp/Cntr=0.3,0.1

Type RM Length L Ch R = 1 ,11614.9 ,93.5,93.5,93.5
XS GIS Cut Line= 4
     1796873.951      432942.159     1796742.006      433261.603
     1796696.868      433390.076      1796637.84      433718.201
#Sta/Elev= 30
       0  957.31    88.9   957.4    98.8  955.26   118.5  954.12     158  949.76
   227.1  947.42   306.1  943.78   365.1   943.1   374.8  941.91  393.67937.9699
     404  937.73   413.7  938.26   433.2  946.22   442.9  948.87   452.6  949.47
   462.3   960.4   472.1  972.84   481.8  979.92   491.6  982.04   511.2  983.19
     521  983.08     570   980.2   619.1   980.2   648.5  978.05   697.5  985.36
   717.1  986.74   736.7  988.97   766.2  990.24   795.6  992.85   815.2  993.51
#Mann= 3 , 0 , 0
       0     .05       0  393.67    .045       0   413.7     .05       0
Bank Sta=393.67,413.7
XS Rating Curve= 0 ,0
Exp/Cntr=0.3,0.1

Type RM Length L Ch R = 1 ,11521.5 ,435.7,416.9,397.7
XS GIS Cut Line= 4
     1796781.937      432938.687     1796649.993      433258.131
     1796604.854      433386.603     1796568.468      433729.775
#Sta/Elev= 30
       0  956.84    39.5  955.86    98.8   955.4   148.1  953.69   167.9  952.43
   227.1  950.64   325.9  949.36   355.4  948.52   365.1   947.3  393.85937.6122
     404  937.35  414.35937.4792   423.4  939.14   442.9  945.31   452.6  947.06
   462.3  947.76   491.6  948.41     541  948.84   600.1   948.4   619.8  949.46
   639.6   951.6   659.3  954.67   708.6  964.88   718.4  965.57   728.3  965.16
     748  963.22   757.9  963.28   777.6  965.43   807.2  969.83   826.9  971.01
#Mann= 3 , 0 , 0
       0     .05       0  393.85    .045       0  414.35     .05       0
Bank Sta=393.85,414.35
XS Rating Curve= 0 ,0
Exp/Cntr=0.3,0.1

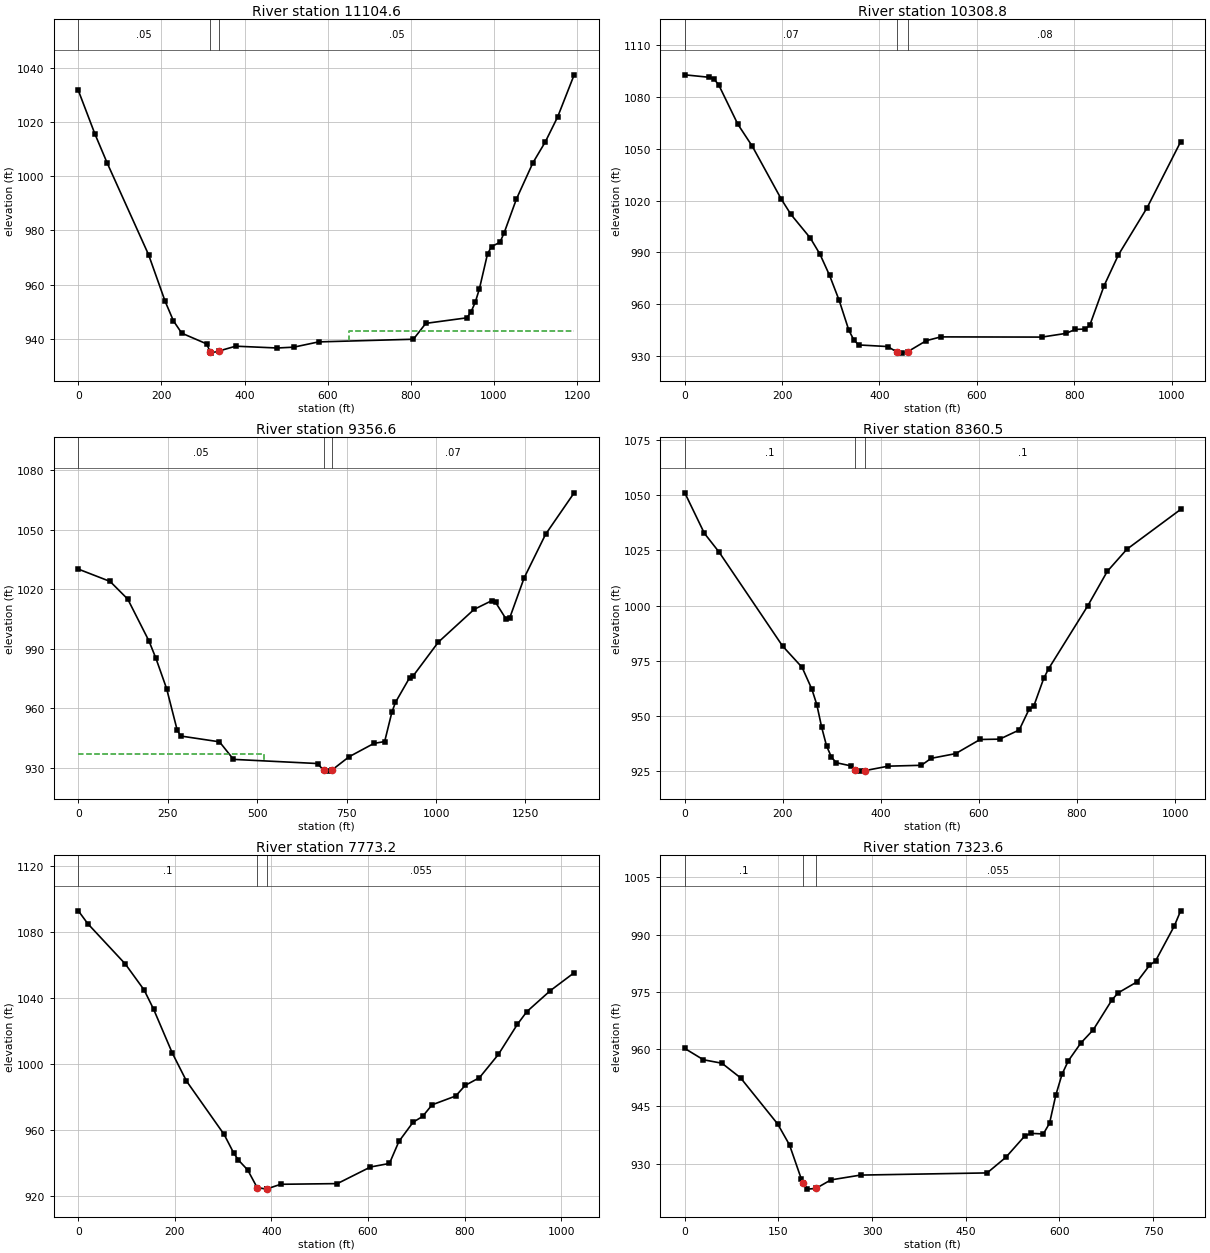
Type RM Length L Ch R = 1 ,11104.6 ,809.1,795.8,781.5
XS GIS Cut Line= 4
      1796018.12      433023.177     1796163.954      433186.372
     1796327.148        433495.4     1796584.093      434064.844
#Sta/Elev= 30
       0 1031.55    39.8 1015.55    69.6 1004.74   169.1  970.98   208.9  953.81
   228.8  946.64   248.8  942.09   308.7  938.14   317.5935.1392   318.7  934.73
     339  935.54   378.6  937.29   478.5  936.62   518.4  936.93   578.2  938.87
   806.3  939.85   836.1   945.7   935.2  947.75   945.2  950.02   955.1  953.47
     965  958.38   984.8  971.42   994.7  974.03  1014.6   975.6  1024.5  979.01
  1054.2  991.54  1093.9  1004.9  1123.6 1012.57  1153.4  1021.8  1193.1 1037.31
#Mann= 3 , 0 , 0
       0     .05       0   317.5    .045       0     339     .05       0
#XS Ineff= 2 , 0
                          652.17          942.75
Permanent Ineff=
       F       F
Bank Sta=317.5,339
XS Rating Curve= 0 ,0
Exp/Cntr=0.3,0.1

Type RM Length L Ch R = 1 ,10308.8 ,960.1,952.2,943.5
XS GIS Cut Line= 4
     1795556.315      433842.622     1795896.593      433950.261
     1796122.287      434096.094      1796455.62      434304.427
#Sta/Elev= 30
       0 1092.97    49.6 1091.56    59.5  1090.6    69.4  1087.3     109 1064.28
   138.8 1051.46   198.3 1020.79   218.1 1011.95   257.8  998.28   277.6  988.94
   297.4  976.61   317.2  962.06   337.1  944.68     347  939.31   356.9  936.23
   416.6  935.29   436.5  932.05   446.5  931.47   458.6  932.39   496.2  938.71
   526.1  940.89   733.7  940.78   782.8  942.91   802.5  945.24   822.2  945.44
     832   947.6   861.5  970.62   890.9   988.5   949.9 1015.89  1018.7  1054.1
#Mann= 3 , 0 , 0
       0     .07       0   436.5    .045       0   458.6     .08       0
Bank Sta=436.5,458.6
XS Rating Curve= 0 ,0
Exp/Cntr=0.3,0.1

Type RM Length L Ch R = 1 ,9356.6  ,988.2,996,1004.4
XS GIS Cut Line= 4
     1795221.245       434535.33     1795585.829      434658.594
     1795960.829      434771.441     1796554.579       434910.33
#Sta/Elev= 30
       0 1030.08    88.8 1023.88   138.2 1014.97   197.4  993.95   217.1  985.12
   246.7  970.02   276.3  949.16   286.2  946.13   394.6  943.21   433.8  934.38
   668.8  932.29   685.5  928.92   698.2  928.47   709.3  929.05   756.9  935.69
   826.4  942.41   856.4  943.35   876.4  957.96   886.4  962.99   926.4  975.53
   936.4  976.44  1006.4  993.33  1106.4 1009.82  1156.3 1014.24  1166.3  1013.4
  1196.3 1004.85  1206.3 1005.66  1246.3 1025.63  1306.3 1047.58  1386.2 1068.45
#Mann= 3 , 0 , 0
       0     .05       0   685.5    .045       0   709.3     .07       0
#XS Ineff= 2 , 0
          519.02  937.09
Permanent Ineff=
       F       F
Bank Sta=685.5,709.3
XS Rating Curve= 0 ,0
Exp/Cntr=0.3,0.1

Type RM Length L Ch R = 1 ,8360.5  ,591.9,587.3,582.3
XS GIS Cut Line= 4
     1795150.065       435249.74      1795446.94      435335.677
     1795587.565       435437.24     1796064.127      435666.407
#Sta/Elev= 30
       0 1051.07    39.9 1032.76    69.8  1024.3   199.4  981.76   239.3  972.09
   259.2  962.21   269.2  955.28   279.2  944.98   289.1   936.6   299.1  931.46
   309.1  928.96     338  927.57   347.6  925.79   357.2  925.16   366.9  925.37
   415.1  927.41   482.5   927.8   502.5  930.95   552.4  933.08   602.3  939.48
   642.2  939.63   682.1  943.78     702  953.06     712  954.71     732  967.07
   741.9  971.44   821.8  999.91   861.7 1015.54   901.6 1025.53  1011.3 1043.55
#Mann= 3 , 0 , 0
       0      .1       0   347.6    .045       0   366.9      .1       0
Bank Sta=347.6,366.9
XS Rating Curve= 0 ,0
Exp/Cntr=0.3,0.1

Type RM Length L Ch R = 1 ,7773.2  ,462.2,449.6,434.5
XS GIS Cut Line= 4
     1794936.523      435674.219      1795196.94      435754.948
     1795423.502      435846.094     1795881.836      436070.052
#Sta/Elev= 30
       0    1093    19.5 1085.21    97.4 1060.69   136.3 1044.94   155.8 1033.34
   194.7 1006.62     224  989.66     302  957.22   321.5  946.14   331.2  941.81
   350.8  935.68   370.3  925.02   389.9  924.05  391.01924.2399   419.2  926.99
   536.5   927.4   605.1  937.48   644.4  939.64     664     953   693.4  964.69
     713  968.15   732.7  975.23   781.7  980.59   801.3  987.03   830.8  991.69
     870  1005.8   909.3 1024.05   928.9 1031.78   977.9 1044.61    1027 1055.41
#Mann= 3 , 0 , 0
       0      .1       0   370.3    .045       0  391.01    .055       0
Bank Sta=370.3,391.01
XS Rating Curve= 0 ,0
Exp/Cntr=0.3,0.1

Type RM Length L Ch R = 1 ,7323.6  ,40.1,39.8,42.5
XS GIS Cut Line= 5
      1794848.85      436109.115     1794994.683      436079.601
     1795116.211      436060.504     1795298.502      436065.712
     1795619.683      436176.823
#Sta/Elev= 30
       0  960.16    29.8   957.2    59.5  956.29    89.3  952.46   148.8  940.35
   167.7  934.87   186.6  925.94     190  924.99   196.1  923.29  209.88 923.463
     234  925.71   281.4  926.97   484.2  927.54   514.2  931.64   544.1  937.16
   554.1  937.91   574.1  937.75   584.1  940.57   594.1  947.92   604.1  953.41
   614.1  956.91   634.1  961.56   654.1  965.05   684.1  972.91   694.1  974.75
   724.1  977.61     744  981.91     754  983.16     784   992.3     794  996.24
#Mann= 3 , 0 , 0
       0      .1       0     190    .045       0  209.88    .055       0
Bank Sta=190,209.88
XS Rating Curve= 0 ,0
Exp/Cntr=0.3,0.1

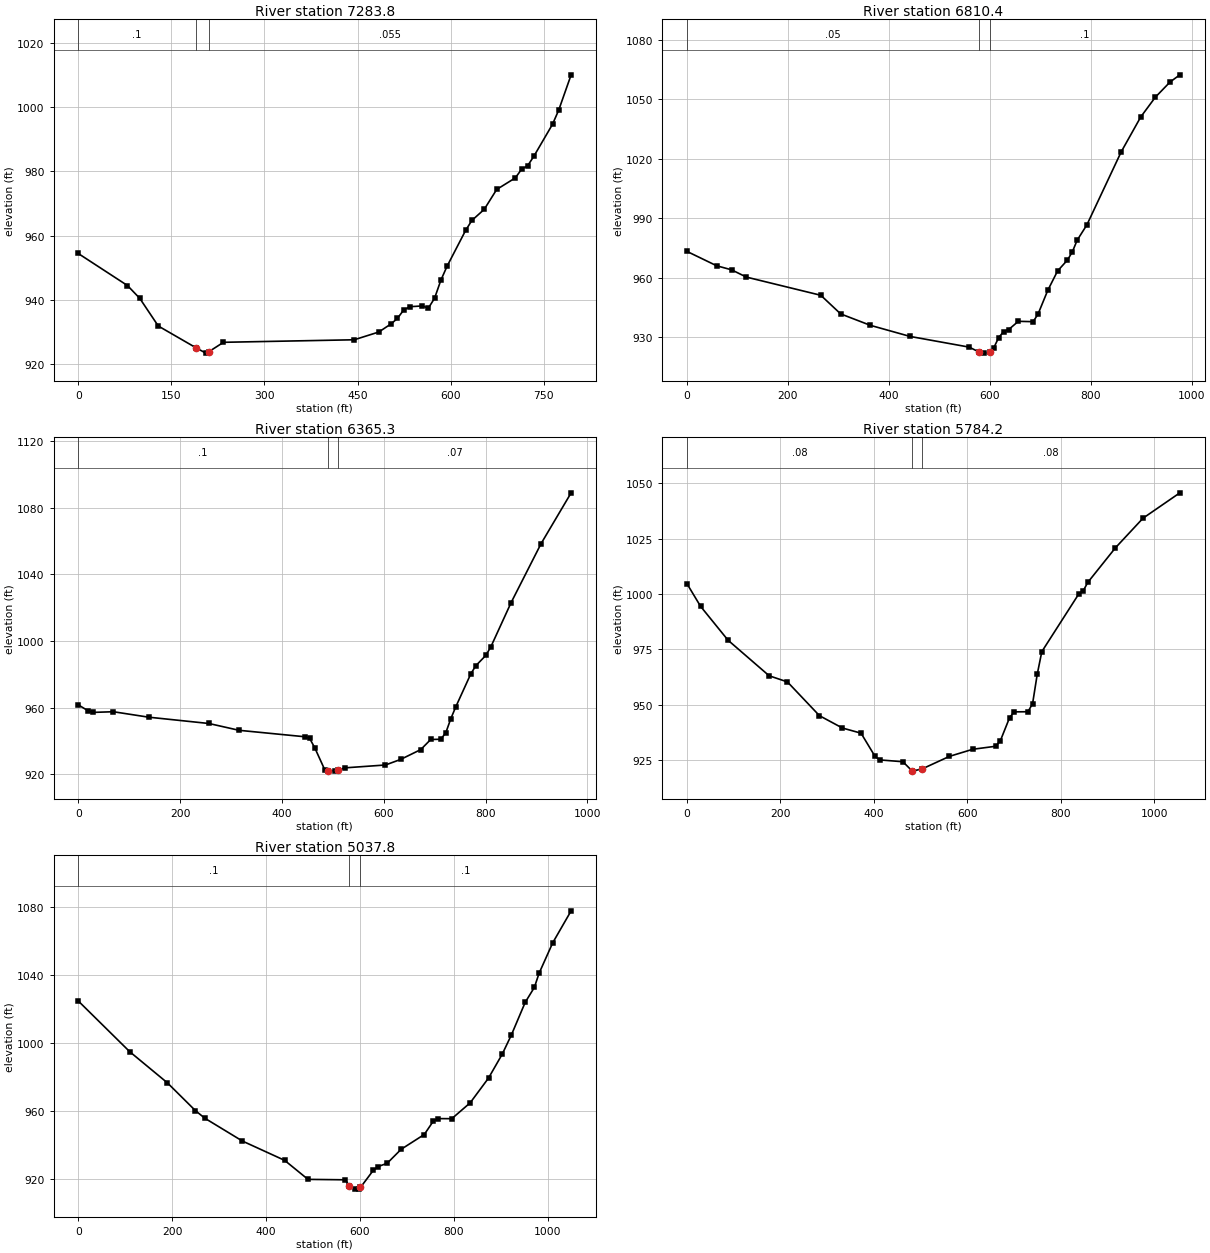
Type RM Length L Ch R = 1 ,7283.8  ,461.9,473.4,483.1
XS GIS Cut Line= 5
     1794841.037      436148.177      1794986.87      436118.664
     1795108.398      436099.566      1795290.69      436104.775
      1795611.87      436215.886
#Sta/Elev= 30
       0  954.41    79.4  944.39    99.2  940.39     129  931.76   190.2  924.91
   205.6  923.29  210.38923.7222     234  926.67   444.6  927.46   484.2  929.88
   504.2  932.45   514.2  934.13   524.2  936.73   534.1  937.78   554.1  938.02
   564.1  937.35   574.1  940.45   584.1  946.02   594.1  950.39   624.1  961.62
   634.1  964.71   654.1  968.19   674.1  974.39   704.1     978   714.1  980.67
   724.1  981.83   734.1   984.8     764  994.73     774  999.17     794 1010.18
#Mann= 3 , 0 , 0
       0      .1       0   190.2    .045       0  210.38    .055       0
Bank Sta=190.2,210.38
XS Rating Curve= 0 ,0
Exp/Cntr=0.3,0.1

Type RM Length L Ch R = 1 ,6810.4  ,442.4,445.2,447.9
XS GIS Cut Line= 4
      1794569.77       436189.41     1795019.423      436331.771
     1795216.905      436385.157     1795494.683       436499.74
#Sta/Elev= 30
       0  973.35      59  966.08    88.4  964.05   117.9  960.37   265.3  951.19
   304.6   941.8   363.6  936.02   442.2  930.42   559.3  925.03   578.8  922.57
   588.6     922  599.69922.4283     608  924.69   617.8  929.86   627.5  932.89
   637.3  933.85   656.7  938.06   685.9  937.87   695.6  941.63     715  953.69
   734.4  963.46   753.8  968.92   763.5     973   773.2  978.97   792.5  986.73
   860.4 1023.54   899.2 1041.19   928.2 1051.17   957.3 1058.83   976.7 1062.45
#Mann= 3 , 0 , 0
       0     .05       0   578.8    .045       0  599.69      .1       0
Bank Sta=578.8,599.69
XS Rating Curve= 0 ,0
Exp/Cntr=0.3,0.1

Type RM Length L Ch R = 1 ,6365.3  ,582.2,581.1,579.9
XS GIS Cut Line= 4
     1794324.978      436467.188     1794693.034      436580.035
     1794935.655      436668.143     1795218.641      436827.865
#Sta/Elev= 30
       0   961.8    19.7  958.12    29.6  957.23    69.1  957.62   138.2  954.36
   256.6  950.57   315.9  946.48   444.5  942.63   454.5  941.62   464.4   936.1
   484.2  922.81   491.1  922.26   504.1     922  509.64922.6846     524  923.97
   603.4  925.68   633.2  929.02   672.6   934.9   692.3  940.98     712  941.11
   721.9  945.02   731.7  953.43   741.6  960.63   771.1  980.41     781  985.27
   800.6  991.43   810.5  996.63   849.9 1022.93     909 1058.44     968  1088.9
#Mann= 3 , 0 , 0
       0      .1       0   491.1    .045       0  509.64     .07       0
Bank Sta=491.1,509.64
XS Rating Curve= 0 ,0
Exp/Cntr=0.3,0.1

Type RM Length L Ch R = 1 ,5784.2  ,747.3,746.4,743.7
XS GIS Cut Line= 4
     1794017.252      436928.559     1794319.336      437010.157
     1794614.475      437100.434     1794984.266      437326.129
#Sta/Elev= 30
       0 1004.72    29.3  994.44      88  979.16     176  963.09   215.1  960.32
   283.6  945.07   332.8  939.49   372.6  937.16   402.5  926.69   412.5  925.09
   462.2  924.26  481.57920.1706   482.2  920.02   503.3  921.02   561.8  926.69
   611.6  929.89   660.9  931.26   670.8   933.8   690.5  944.19   700.3  946.79
   729.8  946.85   739.7  950.54   749.6  963.75   759.4  973.99   838.2  999.95
     848 1001.48   857.8 1005.28   916.9 1020.89     976 1034.28  1054.8 1045.74
#Mann= 3 , 0 , 0
       0     .08       0  481.57    .045       0   503.3     .08       0
Bank Sta=481.57,503.3
XS Rating Curve= 0 ,0
Exp/Cntr=0.3,0.1

Type RM Length L Ch R = 1 ,5037.8  ,920.1,914.7,909.2
XS GIS Cut Line= 4
     1793799.805      437503.646     1794239.475      437668.143
     1794468.641      437732.379      1794795.03      437834.809
#Sta/Elev= 30
       0 1024.93   109.9  994.97   189.8  976.71   249.7  960.29   269.7  955.83
   349.6  942.41   439.5  931.05   489.3  919.84   568.6  919.59     577  916.16
   588.4   914.1   598.4   914.1     601915.0875   628.1   925.1     638  927.33
   657.8  929.31   687.6  937.56   736.8  946.26   756.3   954.2   766.1  955.62
   795.4  955.57   834.5  964.89   873.6  979.48   902.9  993.61   922.5    1005
   951.8 1024.11   971.3  1032.9   981.1 1041.09  1010.4 1059.17  1049.5 1077.95
#Mann= 3 , 0 , 0
       0      .1       0     577    .045       0     601      .1       0
Bank Sta=577,601
XS Rating Curve= 0 ,0
Exp/Cntr=0.3,0.1