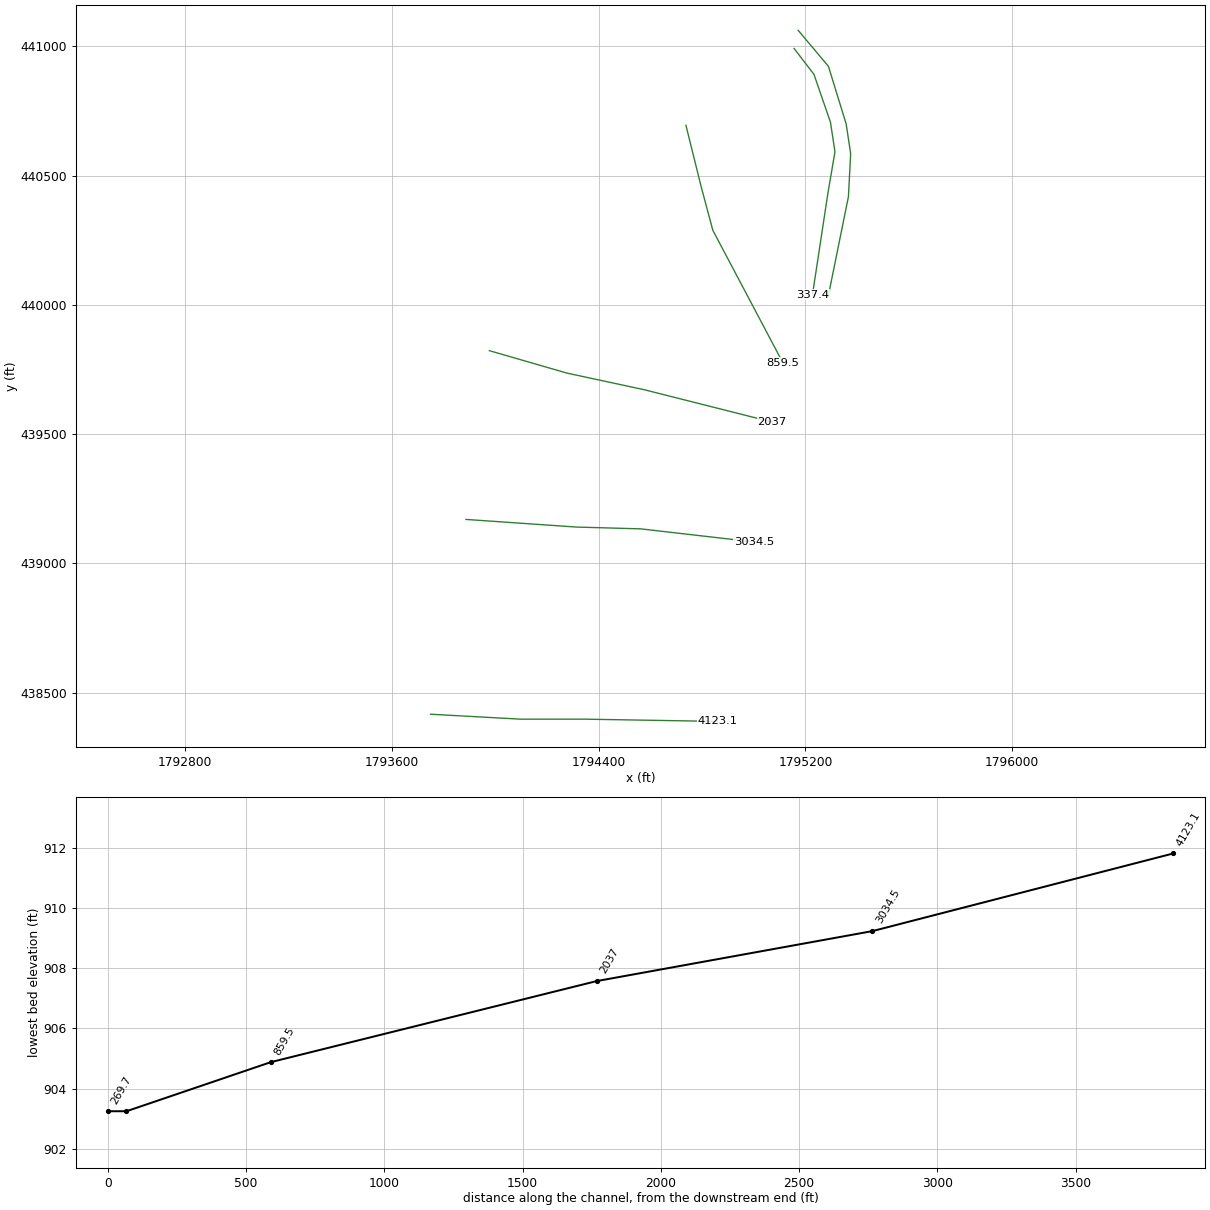
HEC-RAS study DollsRun.prj: DollsRun

--- DollsRun.g01 (geometry) --- (continued)

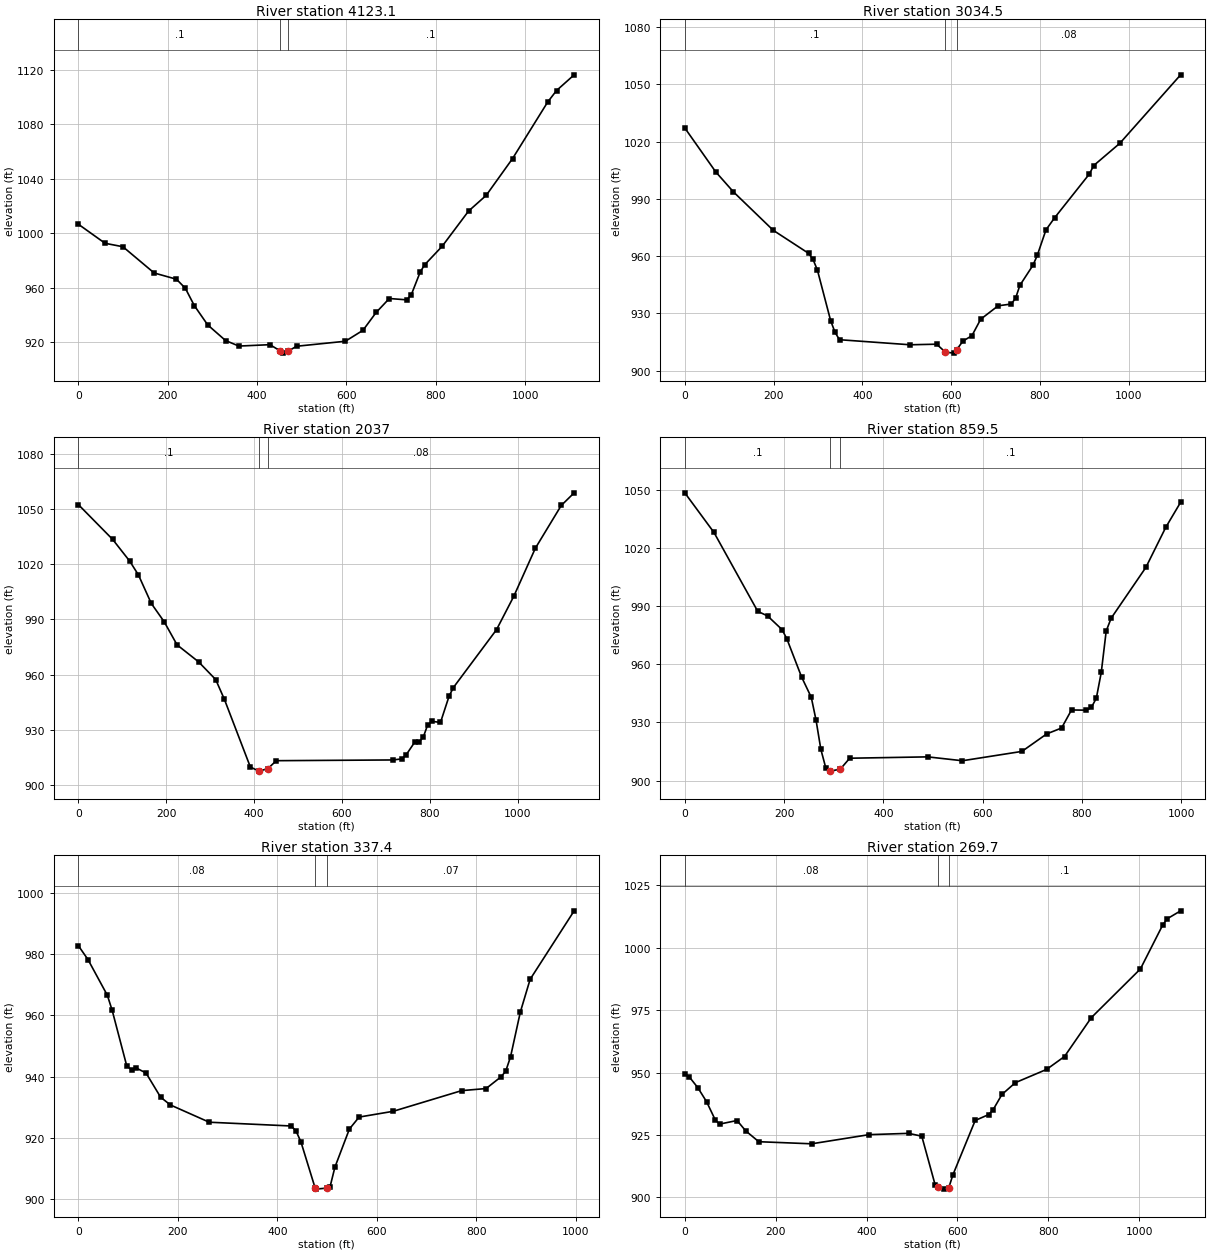
Type RM Length L Ch R = 1 ,4123.1  ,1089.5,1088.6,1087.4
XS GIS Cut Line= 4
     1793749.891      438416.407      1794098.85      438397.309
     1794347.114      438397.309     1794859.266      438388.629
#Sta/Elev= 30
       0 1006.52    59.9  992.49    99.8  989.97   169.8  970.68   219.7   966.1
   239.6  959.43   259.6  946.75   289.6  932.55   329.5  921.08   359.4  916.99
   428.9  918.02   451.9  913.47   458.7  911.81   468.6  913.04   488.5  916.86
   597.8  920.54   637.2  928.57   666.7  941.68   696.2  951.93   735.6  950.94
   745.5   954.8   765.2  971.27     775   976.6   814.5   990.3   873.6 1016.17
     913 1027.67   972.1 1054.74  1050.9 1096.34  1070.6 1104.72    1110 1116.25
#Mann= 3 , 0 , 0
       0      .1       0   451.9    .045       0   468.6      .1       0
Bank Sta=451.9,468.6
XS Rating Curve= 0 ,0
Exp/Cntr=0.3,0.1

Type RM Length L Ch R = 1 ,3034.5  ,1001.7,997.5,1007.7
XS GIS Cut Line= 4
     1793887.044      439169.879     1794314.127      439140.365
     1794562.391      439133.421     1794999.891      439083.073
#Sta/Elev= 30
       0  1027.1    69.7  1004.1   109.5  993.65   199.1  973.55   278.8  961.48
   288.7  958.36   298.7   952.7   328.5  926.23   338.5  920.03   348.5  916.25
   507.6   913.6   567.2  913.91     587  909.73   606.9  909.23   612.3911.0534
   626.8   915.6   646.7  918.35   666.5  926.99   705.8  934.01   735.2  934.93
     745  937.94   754.8  944.74   784.1   955.2   793.9  960.39   813.5  973.75
     833  980.09   911.3 1003.02   921.1 1007.44   979.8 1019.06  1116.8 1054.92
#Mann= 3 , 0 , 0
       0      .1       0     587    .045       0   612.3     .08       0
Bank Sta=587,612.3
XS Rating Curve= 0 ,0
Exp/Cntr=0.3,0.1

Type RM Length L Ch R = 1 ,2037    ,1202.4,1177.6,1148.9
XS GIS Cut Line= 4
     1793977.322      439822.657     1794277.669      439735.851
      1794576.28      439671.615     1795071.072      439546.615
#Sta/Elev= 30
       0 1052.33    78.2 1033.38   117.2 1021.52   136.8 1014.09   166.1  998.61
   195.4  988.68   224.7  976.14   273.6  966.93   312.6   957.3   332.4  946.56
   391.5  909.79   411.2  907.57   431.3  908.92   450.6  913.24   716.2  913.64
   735.8  914.21   745.7   916.3   765.3  923.22   775.1  923.38   784.9  925.95
   794.7  932.47   804.6  934.63   824.2     934   843.8  948.32   853.6  952.98
   951.8  984.42     991 1002.51  1040.1 1028.62    1099 1051.83  1128.4  1058.7
#Mann= 3 , 0 , 0
       0      .1       0   411.2    .045       0   431.3     .08       0
Bank Sta=411.2,431.3
XS Rating Curve= 0 ,0
Exp/Cntr=0.3,0.1

Type RM Length L Ch R = 1 ,859.5   ,532,522,512.1
XS GIS Cut Line= 4
     1794737.739      440694.184     1794796.766      440456.337
     1794841.905      440287.934     1795112.739      439775.782
#Sta/Elev= 30
       0 1048.52    58.8 1028.05     147  987.33   166.6  985.01     196  977.91
   205.8  973.03   235.3  953.44   254.8  942.96   264.4  931.17   274.1  916.08
   283.8  906.74  292.49905.0737   293.5  904.88   313.4  905.94   332.2  911.54
   489.3  912.24   559.2  910.24   679.1  915.06   729.1   924.1     759  927.13
     779  936.45     809  936.34     819  937.76     829  942.52   838.9  955.79
   848.9  977.23   858.9  983.83   928.8 1010.03   968.8 1030.67   998.8 1043.65
#Mann= 3 , 0 , 0
       0      .1       0  292.49    .045       0   313.4      .1       0
Bank Sta=292.49,313.4
XS Rating Curve= 0 ,0
Exp/Cntr=0.3,0.1

Type RM Length L Ch R = 1 ,337.4   ,64.9,67.7,70.4
XS GIS Cut Line= 6
     1795156.141      440991.493     1795232.964      440891.233
     1795296.766      440706.337     1795314.127      440591.754
      1795286.35      440428.559     1795227.322      440039.671
#Sta/Elev= 30
       0  982.73    19.4  978.18    58.3  966.53      68  961.62    97.2  943.55
   106.9  942.15   116.6  942.77   136.1  941.15   165.4  933.26     185  930.73
   263.2  925.09   428.1  923.86   437.8  922.17   447.5  918.65  476.02903.6082
   476.8  903.25  500.44903.5959     506  904.01   515.7  910.38   544.9  922.87
   564.4  926.77   632.8  928.65   770.5   935.4   819.7  936.08   849.2  939.85
     859  941.69   868.8  946.43   888.5  961.05   908.2  971.74   996.7  994.09
#Mann= 3 , 0 , 0
       0     .08       0  476.02    .045       0  500.44     .07       0
Bank Sta=476.02,500.44
XS Rating Curve= 0 ,0
Exp/Cntr=0.3,0.1

Type RM Length L Ch R = 1 ,269.7   ,249.2,269.7,290.3
XS GIS Cut Line= 6
     1795171.766      441061.806     1795288.954      440922.483
      1795357.53      440699.393     1795374.891      440584.809
     1795366.211      440418.143     1795288.086      440032.726
#Sta/Elev= 30
       0  949.41     9.6   948.3    28.8  943.89    47.9  938.31    67.1  930.98
    76.6  929.32     115  930.76   134.2   926.6   162.9  922.26   279.3  921.42
   405.7  925.09   492.7  925.61   521.7  924.47     551  905.03  556.51904.0994
   570.6  903.25  580.85903.6748   590.2  908.97   639.3  930.78   668.8  933.12
   678.6  935.04   698.2  941.21   727.7  945.93   796.5  951.25   835.9  956.42
   894.9     972    1003  991.53  1052.2 1009.19    1062 1011.64  1091.5 1014.82
#Mann= 3 , 0 , 0
       0     .08       0  556.51    .045       0  580.85      .1       0
Bank Sta=556.51,580.85
XS Rating Curve= 0 ,0
Exp/Cntr=0.3,0.1

Chan Stop Cuts=-1
Use User Specified Reach Order=0
Composite Channel Slope=5